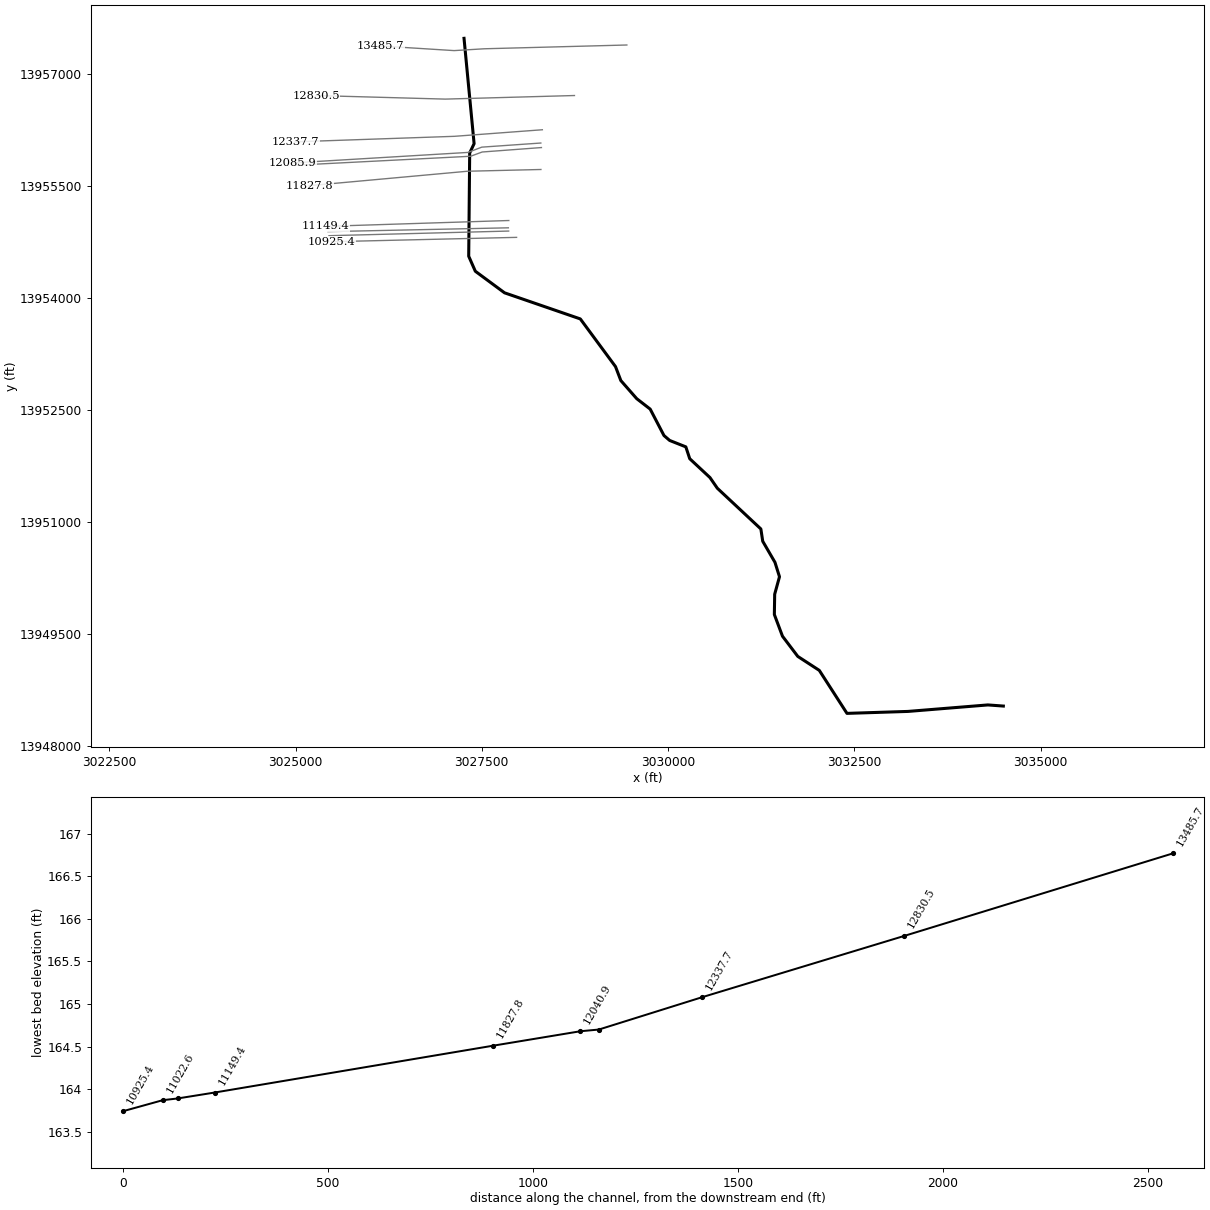
--- M124-00-00.PRJ (project) ---

Proj Title=M124-00-00
Current Plan=p03
Default Exp/Contr=.3,.1
English Units
Geom File=g01
Flow File=f02
Flow File=f03
Plan File=p02
Plan File=p03
Y Axis Title=Elevation
X Axis Title(PF)=Main Channel Distance
X Axis Title(XS)=Station
BEGIN DESCRIPTION:
Willow Creek
Tributary 13.50
HCFCD Unit M124-00-00
Flood Hazard Model
10,2,1,0.2% Event
Filename: M124-00-00.prj
Prepared by: Halff Associates, Inc  Date: 03/05/2004
Reviewed by:                       Date:
STATUS Final RAS
END DESCRIPTION:
DSS Export Rating Curves= 0
DSS Export Rating Curve Sorted= 0
DSS Export Volume Flow Curves= 0
DXF OffsetX= 0
DXF OffsetY= 0
DXF ScaleX= 1
DXF ScaleY= 10

--- M124-00-00.p03 (plan) ---

Plan Title=Floodway
Program Version=3.11
Short Identifier=Floodway0607
Geom File=g01
Flow File=f03
Subcritical Flow
K Sum by GR= 0
Std Step Tol= 0.01
Critical Tol= 0.01
Num of Std Step Trials= 20
Max Error Tol= 0.3
Flow Tol Ratio= 0.001
Split Flow NTrial= 30
Split Flow Tol= 0.02
Split Flow Ratio= 0.02
Log Output Level= 0
Friction Slope Method= 1
Unsteady Friction Slope Method= 2
Unsteady Bridges Friction Slope Method= 1
Parabolic Critical Depth
Global Vel Dist= 0 , 0 , 0
Global Log Level= 0
CheckData=True
Encroach Param=-1 ,5,5, 2
Encroach River=M124-00-00
Encroach Reach=M124-00-00_0023
Encroach Node=13485.7
       1    4905    5650
Encroach Node=12830.5
       1    4905    5760
Encroach Node=12337.7
       1    4945    5820
Encroach Node=12085.9
       1    4950    5840
Encroach Node=12063.4
       1    4950    5820
Encroach Node=12040.9
       1    4950    5800
Encroach Node=11827.8
       1    4955    5790
Encroach Node=11149.4
       1    4980    5730
Encroach Node=11058.6
       1    4980    5735
Encroach Node=11040.6
       1    4980    5735
Encroach Node=11022.6
       1    4980    5735
Encroach Node=10925.4
       1    4980    5725
Encroach Node=10359.2
       1    4970    5540
Encroach Node=9487.4
       1    4963    5630
Encroach Node=8943.7
       1    4946    5540
Encroach Node=8933.2
       1    4946    5540
Encroach Node=8922.7
       1    4946    5540
Encroach Node=8875.4
       1    4954    5530
Encroach Node=8858.4
       1    4960    5530
Encroach Node=8841.4
       1    4963    5530
Encroach Node=8720.5
       1    4881    5550
Encroach Node=8708.0
       1    4870    5550
Encroach Node=8695.5
       1    4850    5550
Encroach Node=8494.3
       1    4700    5655
Encroach Node=8044.3
       1 4648.78 5484.84
Encroach Node=7413.9
       1 4664.04    5500
Encroach Node=6830.6
       1 4668.44 5225.52
Encroach Node=6565.5
       1    4676    5170
Encroach Node=6516.5
       1    4655    5150
Encroach Node=6467.5
       1    4633    5120
Encroach Node=6258.2
       1    4644    5073
Encroach Node=5571.6
       1 4734.01    5110
Encroach Node=5106.2
       1    4510 5058.41
Encroach Node=4613.6
       1    4055    5050
Encroach Node=4112.9
       1    3770  5022.2
Encroach Node=3927.0
       1    3630    5030
Encroach Node=2977.9
       1    3400    5250
Encroach Node=2967.4
       1    3410    5250
Encroach Node=2956.9
       1    3420    5250
Encroach Node=2257.4
       1    3200    5400
Computation Interval=1HOUR
Output Interval=1HOUR
Run HTab= 0
Run UNet= 0
Run PostProcess= 0
UNET Theta= 1
UNET Theta Warmup= 1
UNET ZTol= 0.02
UNET ZSATol= 0.1
UNET MxIter= 20
UNET MaxInSteps= 20
UNET DtIC= 0
UNET DtMin= 0
UNET MaxCRTS= 20
UNET WFStab= 2
UNET SFStab= 1
UNET WFX= 1
UNET SFX= 1
UNET DSS MLevel= 4
UNET DZMax Abort= 100
UNET Convert EG Bridges=-1
UNET Use Existing IB Tables=-1
UNET Froude Reduction=False
UNET Froude Limit= 1
UNET Froude Power= 10
Instantaneous Interval=1HOUR
Write IC File= 0
Echo Input=False
Echo Output=False
Write Detailed= 0
Detailed Automatic Start=False, 10

--- M124-00-00.p02 (plan) ---

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Plan Title=FEMA Effective June 2007
Program Version=3.13
Short Identifier=FEMAeff0607
Geom File=g01
Flow File=f02
Encroach Param=-1 ,0,0, 0

--- M124-00-00.f03 (steady flow) ---

Flow Title=Floodway
Program Version=3.13
Number of Profiles= 2
Profile Names=1PCT_100yr,1PCTFloodway_100yrFW
River Rch & RM=M124-00-00,M124-00-00_0023       ,13485.7
    1800    1800
River Rch & RM=M124-00-00,M124-00-00_0023       ,12085.9
    1930    1930
River Rch & RM=M124-00-00,M124-00-00_0023       ,9487.4
    1960    1960
River Rch & RM=M124-00-00,M124-00-00_0023       ,8875.4
    2080    2080
River Rch & RM=M124-00-00,M124-00-00_0023       ,6565.5
    2240    2240
River Rch & RM=M124-00-00,M124-00-00_0023       ,3927.0
    2336    2336
Boundary for River Rch & Prof#=M124-00-00,M124-00-00_0023       , 1
Up Type= 0
Dn Type= 3
Dn Slope=0.0018
Boundary for River Rch & Prof#=M124-00-00,M124-00-00_0023       , 2
Up Type= 0
Dn Type= 1
Dn Known WS=158.2
DSS Import GetInterval= 0
DSS Import GetPeak= 0
DSS Import FillOption= 0

--- M124-00-00.f02 (steady flow) ---

Flow Title=FEMA Effective June 2007
Program Version=3.13
Number of Profiles= 4
Profile Names=10PCT_10yr, 2PCT_50yr, 1PCT_100yr,0.2PCT_500yr
River Rch & RM=M124-00-00,M124-00-00_0023 ,13485.7
     950    1520    1800    2640
River Rch & RM=M124-00-00,M124-00-00_0023 ,12085.9
     950    1600    1930    2910
River Rch & RM=M124-00-00,M124-00-00_0023 ,9487.4
     950    1620    1960    2980
River Rch & RM=M124-00-00,M124-00-00_0023 ,8875.4
     960    1690    2080    3230
River Rch & RM=M124-00-00,M124-00-00_0023 ,6565.5
     960    1790    2240    3580
River Rch & RM=M124-00-00,M124-00-00_0023 ,3927.0
     964    1848    2336    3808
Boundary for River Rch & Prof#=M124-00-00,M124-00-00_0023 , 1
Up Type= 0
Dn Type= 3
Dn Slope=0.0018
Boundary for River Rch & Prof#=M124-00-00,M124-00-00_0023 , 2
Up Type= 0
Dn Type= 3
Dn Slope=0.0018
Boundary for River Rch & Prof#=M124-00-00,M124-00-00_0023 , 3
Up Type= 0
Dn Type= 3
Dn Slope=0.0018
Boundary for River Rch & Prof#=M124-00-00,M124-00-00_0023 , 4
Up Type= 0
Dn Type= 3
Dn Slope=0.0018
DSS Import GetInterval= 0
DSS Import GetPeak= 0
DSS Import FillOption= 0

--- M124-00-00.g01 (geometry) ---

Geom Title=M124-00-00 June 2007
Program Version=3.13

River Reach=M124-00-00      ,M124-00-00_0023
Reach XY= 30
      3027261.49     13957484.14      3027396.72     13956072.11
      3027337.44     13955946.92      3027324.33     13954563.07
      3027413.31     13954361.68      3027805.23     13954072.61
      3028822.26     13953722.65      3029294.68     13953083.02
      3029365.86     13952896.39       3029579.4     13952653.34
      3029759.96     13952513.58      3029944.85     13952159.41
      3030021.24     13952093.44      3030238.26      13952007.5
       3030290.6     13951848.74      3030562.04     13951596.04
        3030661.     13951452.82       3031245.2     13950906.81
      3031270.37     13950741.88      3031434.43     13950459.76
       3031495.2     13950266.18      3031430.75       13950032.
      3031426.25       13949760.      3031535.37     13949469.25
      3031740.81     13949198.37       3032029.5       13949011.
      3032400.94     13948434.66      3033219.27     13948460.84
      3034291.83     13948547.87      3034499.49     13948532.73

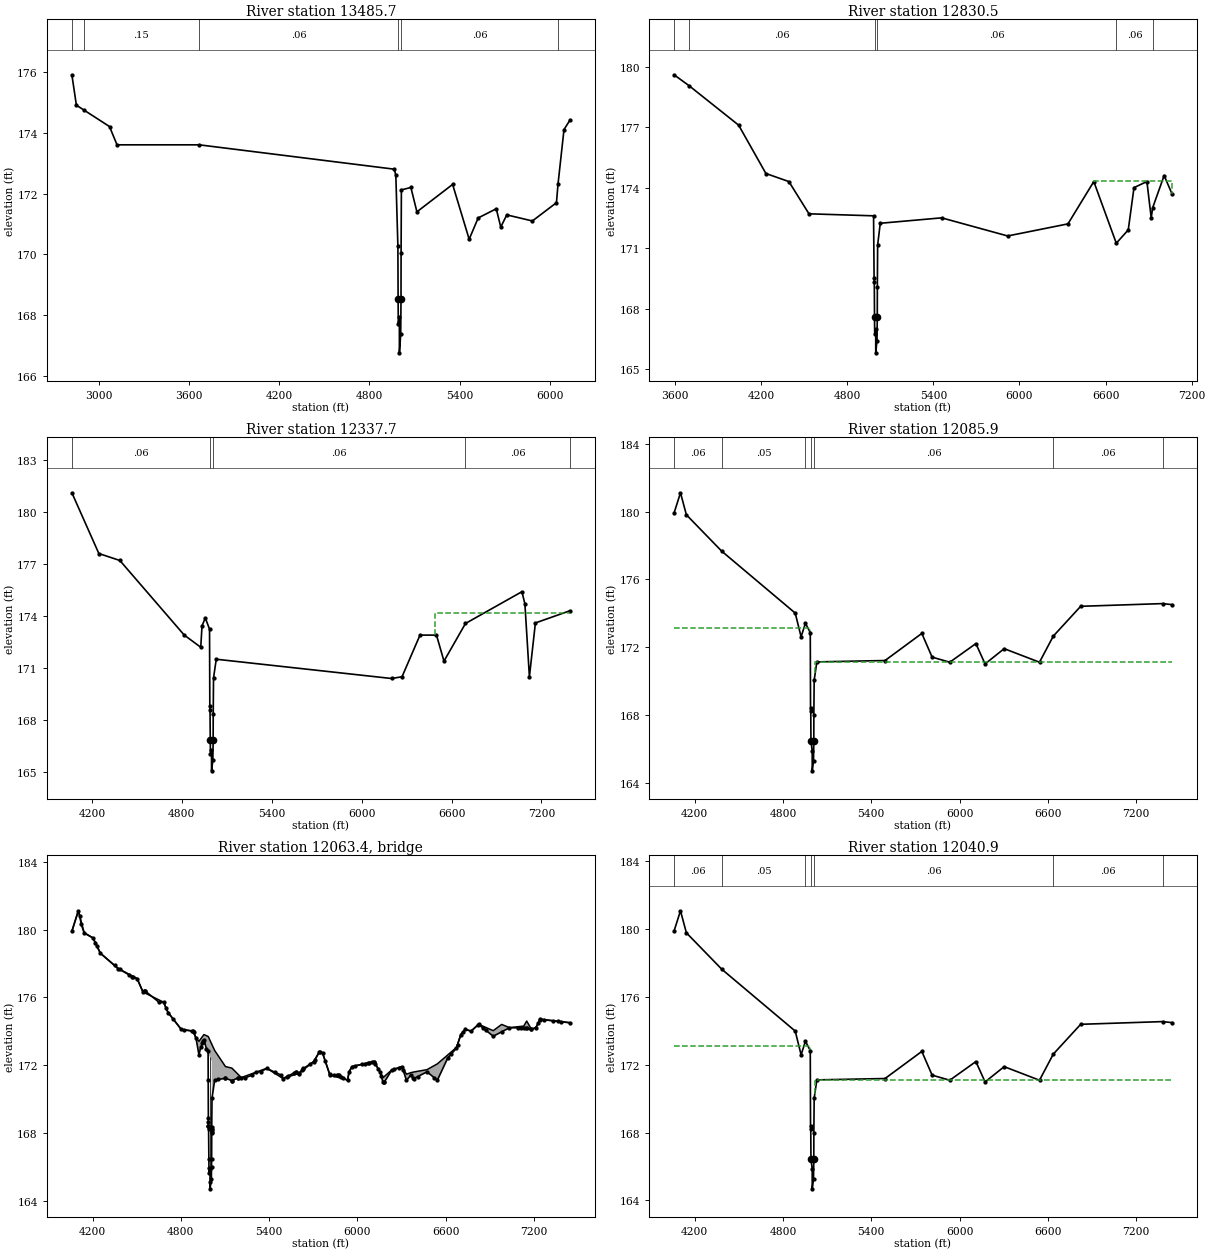
Type RM Length L Ch R = 1 ,13485.7 ,653.8,655.2,663.7
BEGIN DESCRIPTION:
Cross Section XS-05
END DESCRIPTION:
XS GIS Cut Line= 4
      3029446.93      13957394.8      3027535.23      13957344.2
       3027128.7      13957319.7    3026142.3321   13957381.7224
#Sta/Elev= 30
  2822.6   175.9  2852.6   174.9  2900.2  174.75  3072.6   174.2  3122.6   173.6
  3668.6   173.6    4965   172.8    4975   172.6  4988.6  170.28  4990.1  168.53
  4991.4  167.72  4998.4  167.95  4998.7  166.77  5007.4  167.38  5009.4  168.55
  5009.9  170.05  5011.9  172.12    5075   172.2    5115   171.4  5352.2   172.3
  5462.2   170.5  5522.2   171.2  5642.2   171.5  5672.2   170.9  5712.2   171.3
  5882.2   171.1  6042.2   171.7  6052.5  172.31  6092.2   174.1 6130.55   174.4
#Mann= 6 ,-1 , 0
  2822.6      .2       0  2900.2     .15       0  3668.6     .06       0
  4990.1    .055       0  5009.4     .06       0  6052.5      .2       0
Bank Sta=4990.1,5009.4
Exp/Cntr=0.3,0.1

Type RM Length L Ch R = 1 ,12830.5 ,485.94,492.8,514.38
BEGIN DESCRIPTION:
Cross Section XS04.7
END DESCRIPTION:
XS GIS Cut Line= 3
      3028743.47      13956717.5      3027009.85      13956669.4
      3025276.23      13956717.5
#Sta/Elev= 30
  3593.5   179.6  3697.8  179.06  4043.5   177.1  4233.5   174.7  4393.5   174.3
  4533.5   172.7  4983.5   172.6  4987.2  169.51  4988.6  169.31  4990.1  167.56
  4991.4  166.75  4998.4  166.98  4998.7   165.8  5007.4  166.41  5009.4  167.58
  5009.9  169.08  5011.9  171.15  5030.1  172.23  5457.8   172.5  5917.8   171.6
  6337.8   172.2  6517.8   174.3  6674.5  171.24  6757.8   171.9  6797.8     174
  6887.8   174.3  6917.8   172.5  6928.4  173.01  7007.8   174.6  7062.1   173.7
#Mann= 6 ,-1 , 0
  3593.5     .15       0  3697.8     .06       0  4990.1    .055       0
  5009.4     .06       0  6674.5     .06       0  6928.4      .2       0
#XS Ineff= 2 , 0
       0                 6519.01       0  174.31
Permanent Ineff=
       F       F
Bank Sta=4990.1,5009.4
Exp/Cntr=0.3,0.1

Type RM Length L Ch R = 1 ,12337.7 ,154.4,251.8,159.53
BEGIN DESCRIPTION:
Cross Section XS-04.9-Bridge5-con
END DESCRIPTION:
XS GIS Cut Line= 3
      3028312.71      13956258.6      3027132.97      13956170.6
      3024994.99      13956096.6
#Sta/Elev= 30
  4066.7   181.1  4246.7   177.6  4386.7   177.2  4816.7   172.9  4926.7   172.2
  4935.1  173.43    4957  173.89  4985.3  173.24  4987.2  168.79  4988.6  168.59
  4990.1  166.84  4991.4  166.03  4998.4  166.26  4998.7  165.08  5007.4  165.69
  5009.4  166.86  5009.9  168.36  5011.9  170.43  5030.1  171.51  6199.7   170.4
  6269.7   170.5  6389.7   172.9  6499.7   172.9  6549.7   171.4  6693.1  173.57
  7069.7   175.4  7089.7   174.7  7119.7   170.5  7159.7   173.6    7389   174.3
#Mann= 5 ,-1 , 0
  4066.7     .06       0  4990.1    .055       0  5009.4     .06       0
  6693.1     .06       0    7389      .2       0
#XS Ineff= 2 , 0
       0                 6492.63       0  174.15
Permanent Ineff=
       F       F
Bank Sta=4990.1,5009.4
Exp/Cntr=0.5,0.3

Type RM Length L Ch R = 1 ,12085.9 ,45,45,45
BEGIN DESCRIPTION:
Upstream Section of Bridge/Culvert/Weir
END DESCRIPTION:
XS GIS Cut Line= 4
      3028292.11      13956080.7      3027499.68      13956025.5
      3027314.43      13955954.7      3024958.35      13955813.7
#Sta/Elev= 30
  4059.2  179.91    4103  181.11    4143  179.81  4383.8  177.66    4883  174.01
    4923  172.61  4952.3  173.41  4985.3  172.86  4987.1  168.41  4988.6  168.21
  4990.1  166.46  4998.4  165.88  4998.7   164.7  5007.4  165.31  5009.4  166.48
  5009.6  167.98  5011.9  170.05  5030.1  171.13  5493.7  171.21  5743.7  172.81
  5813.7  171.41  5933.7  171.11  6111.2  172.21  6173.7  171.01  6303.7  171.91
  6543.7  171.11  6637.4  172.65  6823.7  174.41  7381.2  174.57    7444  174.51
#Mann= 7 ,-1 , 0
  4059.2     .06       0  4383.8     .05       0  4952.3     .06       0
  4990.1    .055       0  5009.4     .06       0  6637.4     .06       0
  7381.2      .2       0
#XS Ineff= 2 , 0
       0  4980.1  173.13  5019.4       0  171.11
Permanent Ineff=
       F       F
Bank Sta=4990.1,5009.4
Exp/Cntr=0.5,0.3

Type RM Length L Ch R = 3 ,12063.4 ,,,
BEGIN DESCRIPTION:
TRIECHEL ROAD
Structure ID: M124-00-00-06
END DESCRIPTION:
Bridge Culvert--1,0,-1,-1, 0
Deck Dist Width WeirC Skew NumUp NumDn MinLoCord MaxHiCord MaxSubmerge Is_Ogee
10,25,2.6,0, 60, 60, , , 0.95, 0, 1,1,,
  4059.2    4103    4143    4203    4253    4373    4503    4543    4683    4713
    4803    4883    4903    4923    4957  4985.3 4986.91    4987 5009.79  5009.9
  5011.9  5030.1  5103.4    5147  5211.2  5383.7  5493.7  5603.7  5703.7  5743.7
  5763.7  5813.7  5933.7  5943.7  5963.7  6111.2  6153.7  6173.7  6233.7  6303.7
  6333.7  6363.7  6383.7  6473.7  6543.7  6613.7  6673.7  6703.7  6733.7  6773.7
  6823.7  6923.7  6981.2  7033.7  7131.2  7151.2  7183.7  7213.7  7243.7    7444
   179.9  181.11  179.81  179.51  178.61  177.71  177.11  176.31  175.71  175.11
  174.11  174.01  173.61   173.4   173.8  173.69  173.68  173.67  173.24  173.24
   173.2  172.86  171.91  171.82  171.26  171.81  171.21  171.51  172.21  172.81
  172.71  171.41  171.11  171.61  171.91  172.21  171.61  171.25  171.71  171.91
  171.46  171.55  171.59  171.73  172.07  172.59  173.04  173.81  174.11  174.01
  174.41  174.03   174.4  174.21   174.3   174.6  174.11  174.23  174.71   174.5
   179.9   181.1   179.8   179.5   178.6   177.7   177.1   176.3   175.7   175.1
   174.1     174   173.6   172.6   173.5  172.85  168.87  172.67  172.24  168.24
  170.04  171.12  171.22  171.08  171.25   171.8   171.2   171.5   172.2   172.8
   172.7   171.4   171.1   171.6   171.9   172.2   171.6     171   171.7   171.9
   171.1   171.4   171.2   171.6   171.1   172.4     173   173.8   174.1     174
   174.4   173.7  173.96   174.2   174.2  174.18   174.1   174.2   174.7   174.5
  4059.2    4103    4143    4203    4253    4373    4503    4543    4683    4713
    4803    4883    4903    4923    4957  4985.3 4986.91    4987 5009.79  5009.9
  5011.9  5030.1  5103.4    5147  5211.2  5383.7  5493.7  5603.7  5703.7  5743.7
  5763.7  5813.7  5933.7  5943.7  5963.7  6111.2  6153.7  6173.7  6233.7  6303.7
  6333.7  6363.7  6383.7  6473.7  6543.7  6613.7  6673.7  6703.7  6733.7  6773.7
  6823.7  6923.7  6981.2  7033.7  7131.2  7151.2  7183.7  7213.7  7243.7    7444
   179.9  181.11  179.81  179.51  178.61  177.71  177.11  176.31  175.71  175.11
  174.11  174.01  173.61   173.4   173.8  173.69  173.68  173.67  173.24  173.24
   173.2  172.86  171.91  171.82  171.26  171.81  171.21  171.51  172.21  172.81
  172.71  171.41  171.11  171.61  171.91  172.21  171.61  171.25  171.71  171.91
  171.46  171.55  171.59  171.73  172.07  172.59  173.04  173.81  174.11  174.01
  174.41  174.03   174.4  174.21   174.3   174.6  174.11  174.23  174.71   174.5
   179.9   181.1   179.8   179.5   178.6   177.7   177.1   176.3   175.7   175.1
   174.1     174   173.6   172.6   173.5  172.85  168.87  172.67  172.24  168.24
  170.04  171.12  171.22  171.08  171.25   171.8   171.2   171.5   172.2   172.8
   172.7   171.4   171.1   171.6   171.9   172.2   171.6     171   171.7   171.9
   171.1   171.4   171.2   171.6   171.1   172.4     173   173.8   174.1     174
   174.4   173.7  173.96   174.2   174.2  174.18   174.1   174.2   174.7   174.5
Pier Skew, UpSta & Num, DnSta & Num=  ,4998.5, 2 ,4998.5, 2 , 0 , 0 , 0 ,,
       1       1
  163.71   173.5
       1       1
  163.71   173.5
BR Coef= 1 , 1 , 1 ,1.25, 0 ,,,0.8,0,2,0,
WSPro=,,,, 1 ,,,, 0 ,,,, 0 ,,,,-1 ,-1 ,-1 , 0 , 0 , 0 , 0 , 0
BR U #Sta/Elev= 164
  4059.2   179.9    4103   181.1    4113   180.8    4123   180.3    4143   179.8
    4203   179.5  4219.2  179.21  4229.2  179.03    4253   178.6  4349.2  177.88
    4373   177.7  4383.8  177.65  4449.2  177.32  4469.2  177.22    4473   177.2
    4503   177.1    4543   176.3  4549.2  176.36    4553   176.4  4559.2  176.36
    4653   175.7    4683   175.7  4699.2  175.38    4713   175.1  4749.2   174.7
    4803   174.1  4819.2  174.08  4876.4  174.01    4883     174  4886.4  173.93
    4903   173.6    4923   172.6  4935.1  173.04  4946.4  173.28  4951.8  173.39
  4952.3   173.4    4957   173.5  4974.2  172.96  4985.3  172.85    4986  171.12
 4986.91  168.87    4987  168.65  4987.1   168.4  4987.2  168.39  4988.6   168.2
  4990.1  166.45    4991  165.93  4991.4  165.64  4998.4  165.87  4998.6  165.08
  4998.7  164.69  5007.4   165.3  5008.9  165.98  5009.4  166.47  5009.6  167.97
  5009.7  168.06 5009.79  168.14  5009.9  168.24    5010  168.33  5011.9  170.04
  5030.1  171.12  5055.6  171.15  5103.4  171.22  5103.5  171.22  5146.6  171.08
    5147  171.08  5190.2  171.25  5191.3  171.25  5211.2  171.25  5237.9  171.25
  5283.7   171.4  5313.7   171.6  5343.7   171.6  5383.7   171.8  5441.2  171.57
  5483.7   171.4  5493.7   171.2  5521.2  171.32  5531.2  171.37  5571.2  171.54
  5581.2  171.59  5583.7   171.6  5601.2  171.51  5603.7   171.5  5621.2  171.68
  5631.2  171.78  5633.7   171.8  5681.2  172.07  5703.7   172.2  5711.2  172.31
  5741.2  172.76  5743.7   172.8  5763.7   172.7  5781.2  172.25  5811.2  171.46
  5813.7   171.4  5841.2   171.4  5861.2   171.4  5871.2   171.4  5873.7   171.4
  5891.2  171.31  5901.2  171.26  5933.7   171.1  5943.7   171.6  5963.7   171.9
  5981.2  171.94  6031.2  172.04  6051.2  172.08  6071.2  172.12  6081.2  172.14
  6101.2  172.17  6111.2   172.2  6113.7   172.2  6121.2  172.09  6141.2  171.79
  6153.7   171.6  6161.2  171.38  6173.7     171  6181.2     171  6183.7     171
  6233.7   171.7  6251.2  171.75  6281.2  171.84  6303.7   171.9  6311.2   171.7
  6333.7   171.1  6363.7   171.4  6381.2  171.23  6383.7   171.2  6411.2  171.32
  6473.7   171.6  6521.2  171.26  6543.7   171.1  6613.7   172.4  6637.4  172.64
  6673.7     173  6681.2   173.2  6703.7   173.8  6721.2  173.98  6733.7   174.1
  6773.7     174  6821.2  174.38  6823.7   174.4  6851.2  174.21  6871.2  174.07
  6923.7   173.7  6981.2  173.96  7033.7   174.2  7091.2   174.2  7111.2   174.2
  7131.2   174.2  7143.7   174.2  7151.2  174.18  7181.2  174.11  7183.7   174.1
  7213.7   174.2  7231.2  174.49  7241.2  174.66  7243.7   174.7  7271.2  174.67
  7331.2  174.61  7361.2  174.58  7381.2  174.56    7444   174.5
BR U #Mann= 7
  4059.2     .06  4383.8     .05  4952.3     .06  4990.1     .05  5009.4     .06
  6637.4     .06  7381.2      .2
BR U Banks=4990.1,5009.4
BR D #Sta/Elev= 164
  4059.2   179.9    4103   181.1    4113   180.8    4123   180.3    4143   179.8
    4203   179.5  4219.2  179.21  4229.2  179.03    4253   178.6  4349.2  177.88
    4373   177.7  4383.8  177.65  4449.2  177.32  4469.2  177.22    4473   177.2
    4503   177.1    4543   176.3  4549.2  176.36    4553   176.4  4559.2  176.36
    4653   175.7    4683   175.7  4699.2  175.38    4713   175.1  4749.2   174.7
    4803   174.1  4819.2  174.08  4876.4  174.01    4883     174  4886.4  173.93
    4903   173.6    4923   172.6  4935.1  173.04  4946.4  173.28  4951.8  173.39
  4952.3   173.4    4957   173.5  4974.2  172.96  4985.3  172.85    4986  171.12
 4986.91  168.87    4987  168.65  4987.1   168.4  4987.2  168.39  4988.6   168.2
  4990.1  166.45    4991  165.93  4991.4  165.64  4998.4  165.87  4998.6  165.08
  4998.7  164.69  5007.4   165.3  5008.9  165.98  5009.4  166.47  5009.6  167.97
  5009.7  168.06 5009.79  168.14  5009.9  168.24    5010  168.33  5011.9  170.04
  5030.1  171.12  5055.6  171.15  5103.4  171.22  5103.5  171.22  5146.6  171.08
    5147  171.08  5190.2  171.25  5191.3  171.25  5211.2  171.25  5237.9  171.25
  5283.7   171.4  5313.7   171.6  5343.7   171.6  5383.7   171.8  5441.2  171.57
  5483.7   171.4  5493.7   171.2  5521.2  171.32  5531.2  171.37  5571.2  171.54
  5581.2  171.59  5583.7   171.6  5601.2  171.51  5603.7   171.5  5621.2  171.68
  5631.2  171.78  5633.7   171.8  5681.2  172.07  5703.7   172.2  5711.2  172.31
  5741.2  172.76  5743.7   172.8  5763.7   172.7  5781.2  172.25  5811.2  171.46
  5813.7   171.4  5841.2   171.4  5861.2   171.4  5871.2   171.4  5873.7   171.4
  5891.2  171.31  5901.2  171.26  5933.7   171.1  5943.7   171.6  5963.7   171.9
  5981.2  171.94  6031.2  172.04  6051.2  172.08  6071.2  172.12  6081.2  172.14
  6101.2  172.17  6111.2   172.2  6113.7   172.2  6121.2  172.09  6141.2  171.79
  6153.7   171.6  6161.2  171.38  6173.7     171  6181.2     171  6183.7     171
  6233.7   171.7  6251.2  171.75  6281.2  171.84  6303.7   171.9  6311.2   171.7
  6333.7   171.1  6363.7   171.4  6381.2  171.23  6383.7   171.2  6411.2  171.32
  6473.7   171.6  6521.2  171.26  6543.7   171.1  6613.7   172.4  6637.4  172.64
  6673.7     173  6681.2   173.2  6703.7   173.8  6721.2  173.98  6733.7   174.1
  6773.7     174  6821.2  174.38  6823.7   174.4  6851.2  174.21  6871.2  174.07
  6923.7   173.7  6981.2  173.96  7033.7   174.2  7091.2   174.2  7111.2   174.2
  7131.2   174.2  7143.7   174.2  7151.2  174.18  7181.2  174.11  7183.7   174.1
  7213.7   174.2  7231.2  174.49  7241.2  174.66  7243.7   174.7  7271.2  174.67
  7331.2  174.61  7361.2  174.58  7381.2  174.56    7444   174.5
BR D #Mann= 7
  4059.2     .06  4383.8     .05  4952.3     .06  4990.1     .05  5009.4     .06
  6637.4     .06  7381.2      .2
BR D Banks=4990.1,5009.4
BC Design=,, 0 ,, 0 ,,,,,,
BC HTab HWMax=181.11

Type RM Length L Ch R = 1 ,12040.9 ,213.1,213.1,213.1
BEGIN DESCRIPTION:
Downstream Section of Bridge/Culvert/Weir
END DESCRIPTION:
XS GIS Cut Line= 4
      3028300.18       13956020.      3027504.89      13955960.3
      3027350.14      13955903.4      3025003.38      13955783.5
#Sta/Elev= 30
  4059.2  179.89    4103  181.09    4143  179.79  4383.8  177.64    4883  173.99
    4923  172.59  4952.3  173.39  4985.3  172.84  4987.1  168.39  4988.6  168.19
  4990.1  166.44  4998.4  165.86  4998.7  164.68  5007.4  165.29  5009.4  166.46
  5009.6  167.96  5011.9  170.03  5030.1  171.11  5493.7  171.19  5743.7  172.79
  5813.7  171.39  5933.7  171.09  6111.2  172.19  6173.7  170.99  6303.7  171.89
  6543.7  171.09  6637.4  172.63  6823.7  174.39  7381.2  174.55    7444  174.49
#Mann= 7 ,-1 , 0
  4059.2     .06       0  4383.8     .05       0  4952.3     .06       0
  4990.1    .055       0  5009.4     .06       0  6637.4     .06       0
  7381.2      .2       0
#XS Ineff= 2 , 0
       0 4983.43  173.13 5016.07       0  171.11
Permanent Ineff=
       F       F
Bank Sta=4990.1,5009.4
Exp/Cntr=0.5,0.3

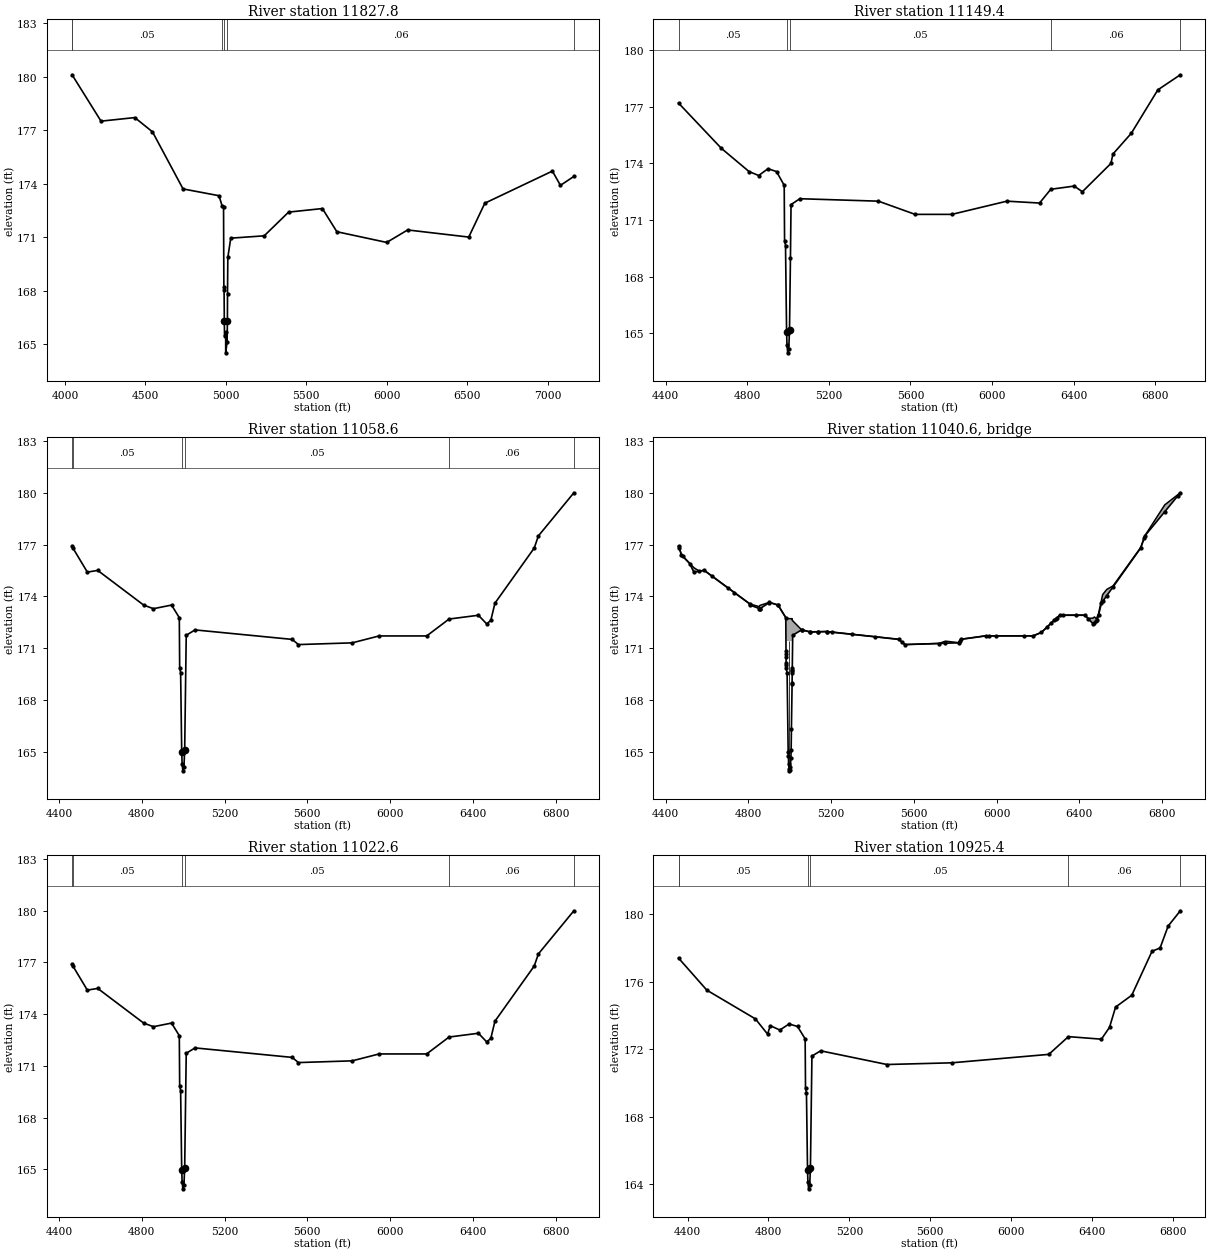
Type RM Length L Ch R = 1 ,11827.8 ,678.71,678.4,666.07
BEGIN DESCRIPTION:
Cross Section XS-04.7-Bridge5-exp
END DESCRIPTION:
XS GIS Cut Line= 3
       3028293.4      13955725.9      3027307.35      13955702.4
      3025182.64      13955508.7
#Sta/Elev= 30
  4043.5   180.1  4223.5   177.5  4433.5   177.7  4543.5   176.9  4733.5   173.7
    4957  173.32  4976.1  172.76  4985.3  172.67  4987.2  168.22  4988.6  168.02
  4990.1  166.27  4991.4  165.46  4998.4  165.69  4998.7  164.51  5007.4  165.12
  5009.4  166.29  5009.9  167.79  5011.9  169.86  5030.1  170.94  5237.9  171.07
  5389.8   172.4  5599.8   172.6  5689.8   171.3  5999.8   170.7  6129.8   171.4
  6509.8     171  6609.8   172.9  7029.8   174.7  7079.8   173.9  7163.3   174.4
#Mann= 6 , 1 , 0
  4043.5      .2       0  4043.5     .05       0  4976.1     .06       0
  4990.1     .05       0  5009.4     .06       0  7163.3      .2       0
Bank Sta=4990.1,5009.4
Exp/Cntr=0.3,0.1

Type RM Length L Ch R = 1 ,11149.4 ,92.8,90.8,83.9
BEGIN DESCRIPTION:
Cross Section XS-04.3-Bridge4-con
END DESCRIPTION:
XS GIS Cut Line= 2
      3027862.36      13955041.9      3025403.36      13954963.5
#Sta/Elev= 30
  4463.2   177.2  4673.2   174.8    4809  173.57  4856.2  173.36  4901.9  173.72
  4943.6  173.57  4981.3  172.84  4983.1  169.91  4987.7  169.65    4993  165.07
  4994.9  164.37  4998.5  163.96  5003.7  164.18  5007.3  165.18  5011.9  168.98
  5014.8  171.82    5058  172.13  5443.2     172  5623.2   171.3  5803.2   171.3
  6073.2     172  6233.2   171.9  6288.3  172.63  6403.2   172.8  6443.2   172.5
  6583.2     174  6593.2   174.5  6683.2   175.6  6813.2   177.9  6923.5   178.7
#Mann= 5 ,-1 , 0
  4463.2     .05       0    4993     .05       0  5007.3     .05       0
  6288.3     .06       0  6923.5      .2       0
Bank Sta=4993,5007.3
Exp/Cntr=0.5,0.3

Type RM Length L Ch R = 1 ,11058.6 ,36,36,36
BEGIN DESCRIPTION:
Upstream Section of Bridge/Culvert/Weir
END DESCRIPTION:
XS GIS Cut Line= 2
      3027856.53       13954944.      3025435.65      13954892.8
#Sta/Elev= 30
    4463  176.91  4466.9  176.81  4536.9  175.41  4586.9  175.51    4809   173.5
  4856.2  173.29  4943.8   173.5  4981.3  172.77  4983.1  169.84  4987.7  169.58
  4992.9     165  4994.9   164.3  4998.5  163.89  5003.7  164.11  5007.3  165.11
  5014.8  171.75  5057.5  172.06  5526.9  171.51  5556.9  171.21  5816.9  171.31
  5946.9  171.71  6176.9  171.71  6285.1  172.69  6426.9  172.91  6466.9  172.41
  6486.9  172.61  6506.9  173.61  6696.9  176.81  6716.9  177.51  6888.3  180.01
#Mann= 6 , 1 , 0
    4463      .2       0  4466.9     .05       0  4992.9     .05       0
  5007.3     .05       0  6285.1     .06       0  6888.3      .2       0
#XS Ineff= 2 , 0
       0    4980  172.68  5017.3       0   171.2
Permanent Ineff=
       F       F
Bank Sta=4992.9,5007.3
Exp/Cntr=0.5,0.3

Type RM Length L Ch R = 3 ,11040.6 ,,,
BEGIN DESCRIPTION:
FIELD ACCESS DS TRIECHEL RD
Structure ID: M124-00-00-05
END DESCRIPTION:
Bridge Culvert--1,0,-1,-1, 0
Deck Dist Width WeirC Skew NumUp NumDn MinLoCord MaxHiCord MaxSubmerge Is_Ogee
10,16,2.6,0, 46, 46, , , 0.95, 0, 1,1,,
    4463  4476.9  4516.9  4536.9    4563  4586.9  4808.9    4853  4856.2  4901.9
  4943.8  4981.3 4982.61  4982.7  5012.5 5012.59  5012.7  5014.8  5057.5  5099.1
    5180  5526.9  5556.9    5723    5753  5816.9  5826.9  5946.9  6176.9  6216.9
  6306.9  6426.9    6443  6466.9    6473    6483  6486.9    6493  6506.9    6513
    6533    6563  6696.9  6716.9    6813  6888.3
   176.9  176.41  175.91  175.66  175.46  175.51  173.55   173.4  173.47  173.65
   173.5  172.77  172.72  172.71   172.7  172.66  172.61  172.58  172.06  171.94
  171.96  171.51   171.2  171.27   171.4  171.31  171.51  171.71  171.71  171.91
  172.91  172.91  172.71  172.74   172.8   172.7  172.82     173  173.76   174.1
   174.4   174.6  176.83  177.51   179.3     180
   176.9   176.4   175.9   175.4  175.45   175.5  173.54  173.29  173.28  173.64
  173.49  172.76  170.63  171.41   171.4  171.36  169.75  171.74  172.05  171.93
  171.95   171.5   171.2  171.26  171.28   171.3   171.5   171.7   171.7   171.9
   172.9   172.9   172.7   172.4  172.46  172.56   172.6  172.91   173.6   173.7
  174.04  174.54   176.8   177.5   178.9     180
    4463  4476.9  4516.9  4536.9    4563  4586.9  4808.9    4853  4856.2  4901.9
  4943.8  4981.3 4982.61  4982.7  5012.5 5012.59  5012.7  5014.8  5057.5  5099.1
    5180  5526.9  5556.9    5723    5753  5816.9  5826.9  5946.9  6176.9  6216.9
  6306.9  6426.9    6443  6466.9    6473    6483  6486.9    6493  6506.9    6513
    6533    6563  6696.9  6716.9    6813  6888.3
   176.9  176.41  175.91  175.66  175.46  175.51  173.55   173.4  173.47  173.65
   173.5  172.77  172.72  172.71   172.7  172.66  172.61  172.58  172.06  171.94
  171.96  171.51   171.2  171.27   171.4  171.31  171.51  171.71  171.71  171.91
  172.91  172.91  172.71  172.74   172.8   172.7  172.82     173  173.76   174.1
   174.4   174.6  176.83  177.51   179.3     180
   176.9   176.4   175.9   175.4  175.45   175.5  173.54  173.29  173.28  173.64
  173.49  172.76  170.63  171.41   171.4  171.36  169.75  171.74  172.05  171.93
  171.95   171.5   171.2  171.26  171.28   171.3   171.5   171.7   171.7   171.9
   172.9   172.9   172.7   172.4  172.46  172.56   172.6  172.91   173.6   173.7
  174.04  174.54   176.8   177.5   178.9     180
Pier Skew, UpSta & Num, DnSta & Num=  ,4998.5, 2 ,4998.5, 2 , 0 , 0 , 0 ,,
       1       1
   162.9  172.37
       1       1
   162.9  172.37
BR Coef= 1 , 1 , 1 ,1.25, 0 ,,,0.8,0,2,0,
WSPro=,,,, 1 ,,,, 0 ,,,, 0 ,,,,-1 ,-1 ,-1 , 0 , 0 , 0 , 0 , 0
BR U #Sta/Elev= 95
    4463   176.9  4466.9   176.8  4476.9   176.4    4483  176.32  4516.9   175.9
  4536.9   175.4    4563  175.45  4586.9   175.5    4623  175.18    4703  174.47
    4733  174.21  4808.9  173.54    4809  173.49    4853  173.29  4856.2  173.28
  4856.6  173.28  4901.2  173.63  4901.9  173.64  4943.6  173.49  4943.8  173.49
  4981.3  172.76  4982.5  170.81 4982.61  170.63  4982.7  170.48  4982.9  170.16
    4983  169.99  4983.1  169.83  4987.7  169.57  4992.9  164.99  4994.1  164.73
  4994.9  164.29  4997.6  163.98  4998.5  163.88  5000.3  163.95  5003.7   164.1
    5006   164.6  5007.3   165.1  5008.6   166.3  5011.8   168.9  5011.9  168.99
  5012.5  169.56 5012.59  169.65  5012.7  169.75  5012.8  169.85  5014.8  171.74
  5057.5  172.05    5058  172.05  5099.1  171.93  5100.8  171.93  5138.8  171.94
    5139  171.94  5179.7  171.95    5180  171.95    5203  171.92    5303  171.79
    5413  171.65  5526.9   171.5    5543  171.34  5556.9   171.2    5723  171.26
    5753  171.28  5816.9   171.3    5823  171.42  5826.9   171.5  5946.9   171.7
    5963   171.7  5996.9   171.7    6133   171.7  6176.9   171.7  6216.9   171.9
    6243   172.2    6263  172.44  6276.9   172.6  6285.1  172.68    6293  172.76
  6306.9   172.9    6323   172.9    6383   172.9  6426.9   172.9    6443   172.7
  6466.9   172.4    6473  172.46    6483  172.56  6486.9   172.6    6493  172.91
  6506.9   173.6    6513   173.7    6533  174.04    6563  174.54  6696.9   176.8
    6713  177.36  6716.9   177.5    6813   178.9  6874.7   179.8  6888.3     180
BR U #Mann= 5
    4463      .2  4466.9     .05  4992.9     .04  5007.3     .05  6285.1     .06
BR U Banks=4992.9,5007.3
BR D #Sta/Elev= 95
    4463   176.9  4466.9   176.8  4476.9   176.4    4483  176.32  4516.9   175.9
  4536.9   175.4    4563  175.45  4586.9   175.5    4623  175.18    4703  174.47
    4733  174.21  4808.9  173.54    4809  173.49    4853  173.29  4856.2  173.28
  4856.6  173.28  4901.2  173.63  4901.9  173.64  4943.6  173.49  4943.8  173.49
  4981.3  172.76  4982.5  170.81 4982.61  170.63  4982.7  170.48  4982.9  170.16
    4983  169.99  4983.1  169.83  4987.7  169.57  4992.9  164.99  4994.1  164.73
  4994.9  164.29  4997.6  163.98  4998.5  163.88  5000.3  163.95  5003.7   164.1
    5006   164.6  5007.3   165.1  5008.6   166.3  5011.8   168.9  5011.9  168.99
  5012.5  169.56 5012.59  169.65  5012.7  169.75  5012.8  169.85  5014.8  171.74
  5057.5  172.05    5058  172.05  5099.1  171.93  5100.8  171.93  5138.8  171.94
    5139  171.94  5179.7  171.95    5180  171.95    5203  171.92    5303  171.79
    5413  171.65  5526.9   171.5    5543  171.34  5556.9   171.2    5723  171.26
    5753  171.28  5816.9   171.3    5823  171.42  5826.9   171.5  5946.9   171.7
    5963   171.7  5996.9   171.7    6133   171.7  6176.9   171.7  6216.9   171.9
    6243   172.2    6263  172.44  6276.9   172.6  6285.1  172.68    6293  172.76
  6306.9   172.9    6323   172.9    6383   172.9  6426.9   172.9    6443   172.7
  6466.9   172.4    6473  172.46    6483  172.56  6486.9   172.6    6493  172.91
  6506.9   173.6    6513   173.7    6533  174.04    6563  174.54  6696.9   176.8
    6713  177.36  6716.9   177.5    6813   178.9  6874.7   179.8  6888.3     180
BR D #Mann= 5
    4463      .2  4466.9     .05  4992.9     .04  5007.3     .05  6285.1     .06
BR D Banks=4992.9,5007.3
BC Design=,, 0 ,, 0 ,,,,,,
BC HTab HWMax=180.01

Type RM Length L Ch R = 1 ,11022.6 ,97.2,97.2,97.2
BEGIN DESCRIPTION:
Downstream Section of Bridge/Culvert/Weir
END DESCRIPTION:
XS GIS Cut Line= 2
      3027860.62      13954900.5      3025449.76      13954838.4
#Sta/Elev= 30
    4463  176.89  4466.9  176.79  4536.9  175.39  4586.9  175.49    4809  173.48
  4856.2  173.27  4943.8  173.48  4981.3  172.75  4983.1  169.82  4987.7  169.56
  4992.9  164.98  4994.9  164.28  4998.5  163.87  5003.7  164.09  5007.3  165.09
  5014.8  171.73  5057.5  172.04  5526.9  171.49  5556.9  171.19  5816.9  171.29
  5946.9  171.69  6176.9  171.69  6285.1  172.67  6426.9  172.89  6466.9  172.39
  6486.9  172.59  6506.9  173.59  6696.9  176.79  6716.9  177.49  6888.3  179.99
#Mann= 6 , 1 , 0
    4463      .2       0  4466.9     .05       0  4992.9     .05       0
  5007.3     .05       0  6285.1     .06       0  6888.3      .2       0
#XS Ineff= 2 , 0
       0    4980  172.68  5017.3       0   171.2
Permanent Ineff=
       F       F
Bank Sta=4992.9,5007.3
Exp/Cntr=0.5,0.3

Type RM Length L Ch R = 1 ,10925.4 ,512.46,566.2,732.56
BEGIN DESCRIPTION:
Cross Section XS-04.1-Bridge4-exp
END DESCRIPTION:
XS GIS Cut Line= 2
      3027966.79       13954816.      3025487.51      13954757.8
#Sta/Elev= 30
  4355.5   177.4  4495.5   175.5  4735.5   173.8  4795.5   172.9  4808.9   173.4
  4856.2  173.14  4901.9   173.5  4943.6  173.35  4981.3  172.62  4983.1  169.69
  4987.7  169.43    4993  164.85  4994.9  164.15  4998.5  163.74  5003.7  163.96
  5007.3  164.96  5014.8   171.6    5058  171.91  5385.5   171.1  5705.5   171.2
  6185.5   171.7  6282.3  172.75  6445.5   172.6  6485.5   173.3  6515.5   174.5
  6595.5   175.2  6695.5   177.8  6735.5     178  6775.5   179.3  6835.5   180.2
#Mann= 6 , 1 , 0
  4355.5      .2       0  4355.5     .05       0    4993     .05       0
  5007.3     .05       0  6282.3     .06       0  6835.5      .2       0
Bank Sta=4993,5007.3
Exp/Cntr=0.3,0.1