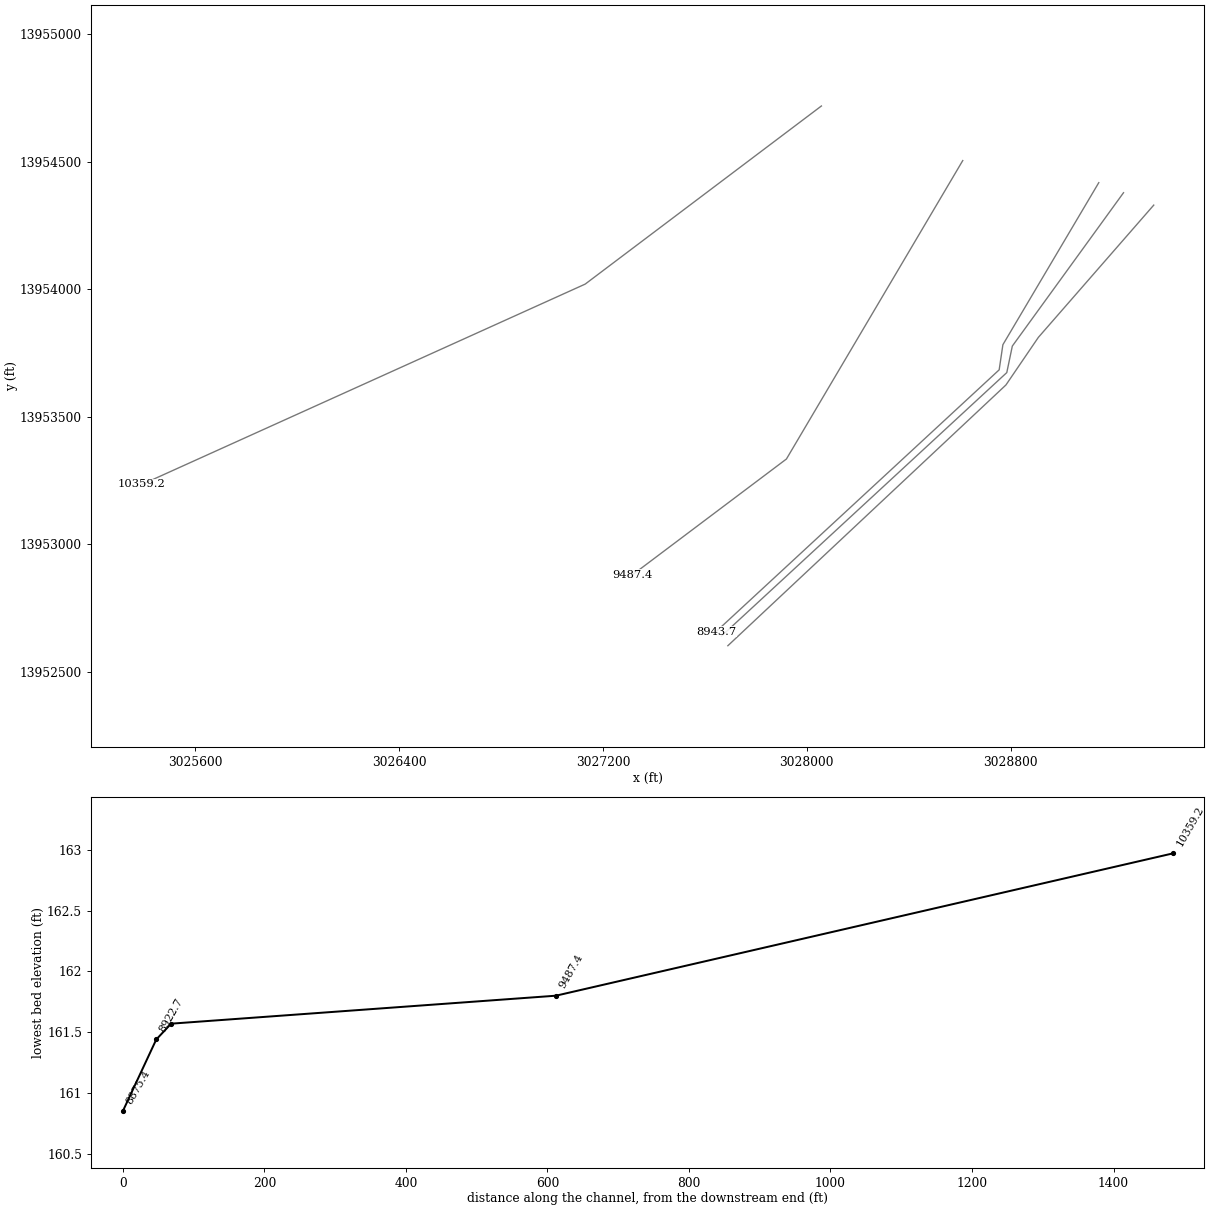
HEC-RAS study M124-00-00.PRJ: M124-00-00

--- M124-00-00.g01 (geometry) --- (continued)

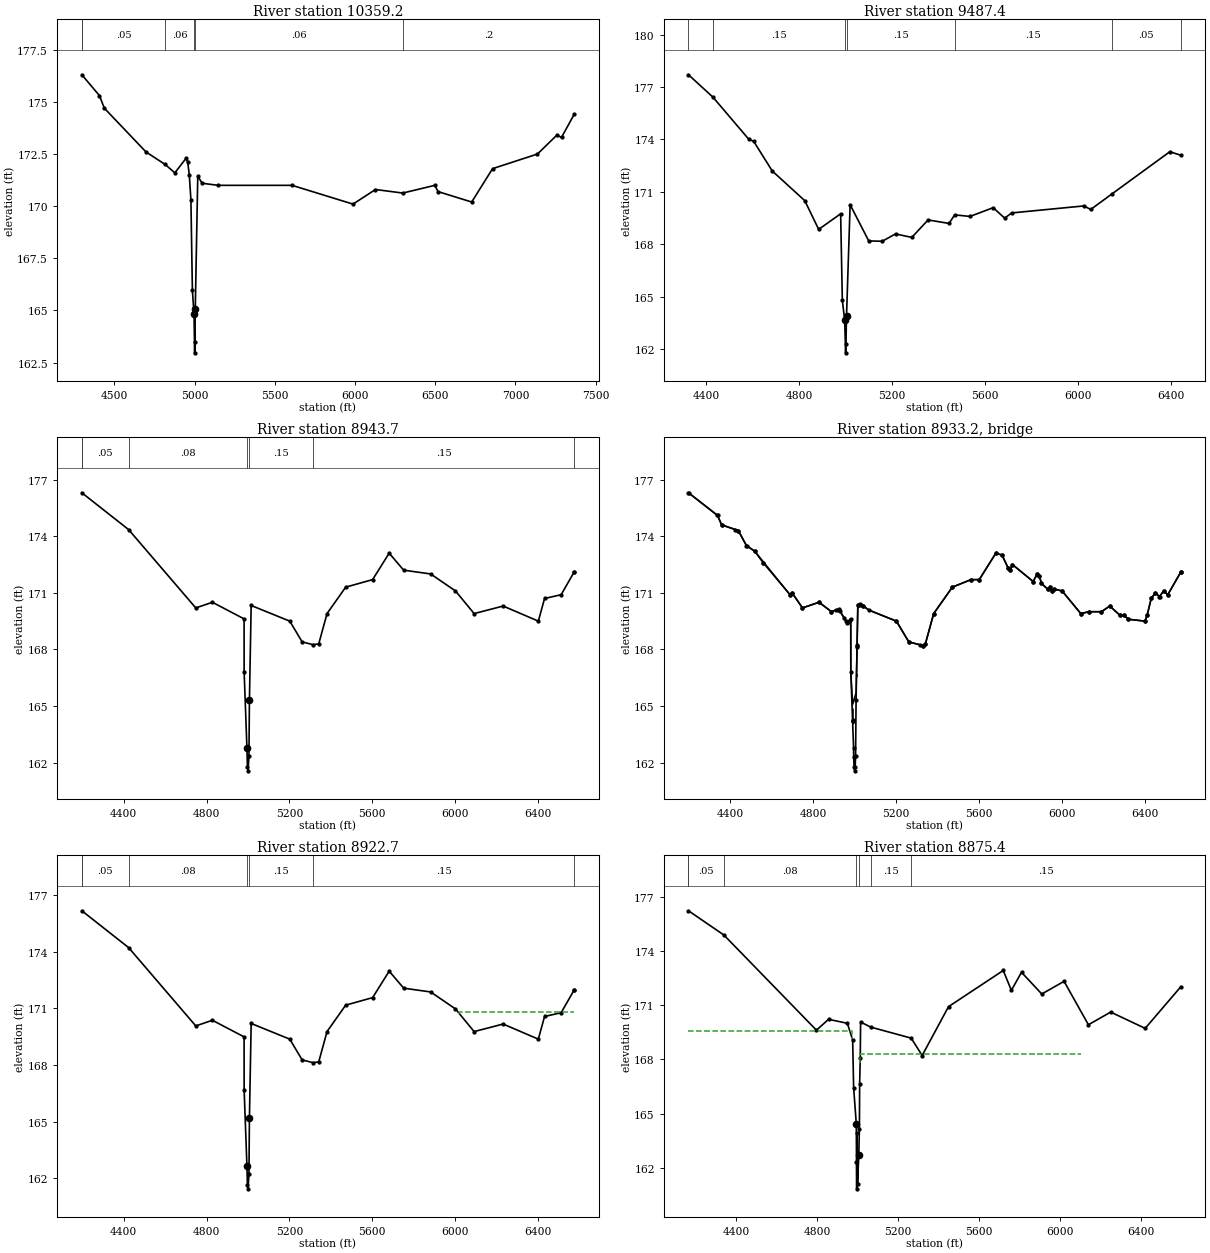
Type RM Length L Ch R = 1 ,10359.2 ,846.98,871.8,985.04
BEGIN DESCRIPTION:
Cross Section XS04.5
END DESCRIPTION:
XS GIS Cut Line= 3
      3028057.24      13954719.1      3027130.24      13954020.8
      3025390.63      13953235.3
#Sta/Elev= 30
  4296.8   176.3  4406.8   175.3  4436.8   174.7  4696.8   172.6  4816.4     172
  4876.8   171.6  4946.8   172.3  4956.8   172.1  4966.8   171.5  4976.8   170.3
    4986  165.97  4996.1  164.84  5000.1  162.97  5001.5   163.5    5004  165.08
  5019.5  171.44  5046.8   171.1  5146.8     171  5607.4     171  5987.4   170.1
  6127.4   170.8  6297.5  170.63  6497.4     171  6517.4   170.7  6727.4   170.2
  6857.4   171.8  7137.4   172.5  7257.4   173.4  7287.4   173.3  7366.1   174.4
#Mann= 6 , 1 , 0
  4296.8      .2       0  4296.8     .05       0  4816.4     .06       0
  4996.1     .05       0    5004     .06       0  6297.5      .2       0
Bank Sta=4996.1,5004
Exp/Cntr=0.3,0.1

Type RM Length L Ch R = 1 ,9487.4  ,542.11,543.7,440.28
BEGIN DESCRIPTION:
Cross Section XS-04
END DESCRIPTION:
XS GIS Cut Line= 3
      3028611.94      13954505.1      3027920.01      13953335.1
      3027314.65      13952880.2
#Sta/Elev= 30
  4324.6   177.7  4429.8  176.42  4584.6     174  4604.6   173.9  4684.6   172.2
  4824.6   170.5  4884.3  168.86  4978.7  169.75    4986   164.8  4996.1  163.67
  5000.1   161.8  5001.5  162.33    5004  163.91  5019.5  170.27  5099.5   168.2
  5157.4  168.18  5214.6   168.6  5284.6   168.4  5354.6   169.4  5444.6   169.2
  5468.9  169.69  5534.6   169.6  5634.6   170.1  5683.9   169.5  5713.9   169.8
  6023.9   170.2  6053.9     170  6143.4  170.87  6393.9   173.3  6441.1   173.1
#Mann= 7 ,-1 , 0
  4324.6     .05       0  4429.8     .15       0  4996.1     .05       0
    5004     .15       0  5468.9     .15       0  6143.4     .05       0
  6441.1      .2       0
Bank Sta=4996.1,5004
Exp/Cntr=0.5,0.3

Type RM Length L Ch R = 1 ,8943.7  ,21,21,21
BEGIN DESCRIPTION:
Upstream Section of Bridge/Culvert/Weir
END DESCRIPTION:
XS GIS Cut Line= 4
      3029145.74      13954418.5      3028769.47      13953783.3
      3028754.85      13953684.7      3027644.35      13952658.8
#Sta/Elev= 30
    4198   176.3  4423.7  174.35    4748   170.2  4828.1   170.5 4981.13  169.62
 4981.43  166.81 4994.93  162.77 4997.23  161.77 5000.23  161.57 5004.63  162.33
 5006.93   165.3 5015.33  170.33  5201.6   169.5  5261.5   168.4  5315.2  168.25
  5341.6   168.3  5381.5   169.9  5471.5   171.3  5601.6   171.7  5681.5   173.1
  5751.5   172.2  5881.6     172  6001.6   171.1  6091.5   169.9  6231.6   170.3
  6401.5   169.5  6431.5   170.7  6511.6   170.9  6574.2   172.1  6574.4   172.1
#Mann= 7 , 1 , 0
    4198      .2       0    4198     .05       0  4423.7     .08       0
 4994.93     .07       0 5006.93     .15       0  5315.2     .15       0
  6574.2      .2       0
#XS Ineff= 2 , 0
       0                    6020       0   170.8
Permanent Ineff=
       F       F
Bank Sta=4994.93,5006.93
Exp/Cntr=0.5,0.3

Type RM Length L Ch R = 3 ,8933.2  ,,,
BEGIN DESCRIPTION:
PL1_M124-00-00-X03B
END DESCRIPTION:
Bridge Culvert--1,0,-1,-1, 0
Deck Dist Width WeirC Skew NumUp NumDn MinLoCord MaxHiCord MaxSubmerge Is_Ogee
10,1,2.6,0, 60, 60, , , 0.95, 0, 1,1,,
    4198  4338.1    4358  4438.1    4478  4518.1    4688  4698.1    4748  4828.1
    4888 4922.73 4965.43 4981.13 4981.43 4989.93 4990.04 4990.13 5006.93 5011.73
 5015.33 5026.23 5068.93  5201.6  5261.5  5331.6  5341.6  5381.5  5471.5  5561.5
  5601.6  5681.5  5711.6  5741.5  5751.5  5761.6  5861.5  5881.6  5891.6  5901.5
  5931.5  5941.6  5951.5  5961.5  6001.6  6091.5  6131.5  6191.6  6231.6  6281.5
  6301.6  6321.5  6401.5  6411.6  6431.5  6451.5  6471.6  6491.5  6511.6  6574.4
   176.3   175.1   174.6   174.3   173.5   173.2   170.9     171   170.2   170.5
     170  170.14   169.4  169.63  166.89  165.12  165.12  165.13   165.7  168.18
  170.34  170.43  170.09   169.5   168.4   168.2   168.3   169.9   171.3   171.7
   171.7   173.1     173   172.3   172.2   172.5   171.6     172   171.9   171.5
   171.2   171.3   171.1   171.2   171.1   169.9     170     170   170.3   169.8
   169.8   169.6   169.5   169.8   170.7     171   170.8   171.1   170.9   172.1
   176.3   175.1   174.6   174.3   173.5   173.2   170.9     171   170.2   170.5
     170  170.13  169.39  169.62  166.81  164.27  164.23  164.88  165.45  168.17
  170.33  170.42  170.08   169.5   168.4   168.2   168.3   169.9   171.3   171.7
   171.7   173.1     173   172.3   172.2   172.5   171.6     172   171.9   171.5
   171.2   171.3   171.1   171.2   171.1   169.9     170     170   170.3   169.8
   169.8   169.6   169.5   169.8   170.7     171   170.8   171.1   170.9   172.1
    4198  4338.1    4358  4438.1    4478  4518.1    4688  4698.1    4748  4828.1
    4888 4922.73 4965.43 4981.13 4981.43 4989.93 4990.04 4990.13 5006.93 5011.73
 5015.33 5026.23 5068.93  5201.6  5261.5  5331.6  5341.6  5381.5  5471.5  5561.5
  5601.6  5681.5  5711.6  5741.5  5751.5  5761.6  5861.5  5881.6  5891.6  5901.5
  5931.5  5941.6  5951.5  5961.5  6001.6  6091.5  6131.5  6191.6  6231.6  6281.5
  6301.6  6321.5  6401.5  6411.6  6431.5  6451.5  6471.6  6491.5  6511.6  6574.4
   176.3   175.1   174.6   174.3   173.5   173.2   170.9     171   170.2   170.5
     170  170.14   169.4  169.63  166.89  165.12  165.12  165.13   165.7  168.18
  170.34  170.43  170.09   169.5   168.4   168.2   168.3   169.9   171.3   171.7
   171.7   173.1     173   172.3   172.2   172.5   171.6     172   171.9   171.5
   171.2   171.3   171.1   171.2   171.1   169.9     170     170   170.3   169.8
   169.8   169.6   169.5   169.8   170.7     171   170.8   171.1   170.9   172.1
   176.3   175.1   174.6   174.3   173.5   173.2   170.9     171   170.2   170.5
     170  170.13  169.39  169.62  166.81  164.27  164.23  164.88  165.45  168.17
  170.33  170.42  170.08   169.5   168.4   168.2   168.3   169.9   171.3   171.7
   171.7   173.1     173   172.3   172.2   172.5   171.6     172   171.9   171.5
   171.2   171.3   171.1   171.2   171.1   169.9     170     170   170.3   169.8
   169.8   169.6   169.5   169.8   170.7     171   170.8   171.1   170.9   172.1
Pier Skew, UpSta & Num, DnSta & Num=  ,4990.6, 2 ,4990.6, 2 , 0 , 0 , 0 ,,
      .5      .5
  162.99  165.91
      .5      .5
  162.99  165.91
Pier Skew, UpSta & Num, DnSta & Num=  ,5009.1, 2 ,5009.1, 2 , 0 , 0 , 0 ,,
      .5      .5
  165.47  167.84
      .5      .5
  165.47  167.84
BR Coef= 1 , 1 , 0 ,1.25, 0 ,,,0.8,-1,2,1,
WSPro=,,,, 1 ,,,, 0 ,,,, 0 ,,,,-1 ,-1 ,-1 , 0 , 0 , 0 , 0 , 0
BR U #Sta/Elev= 133
    4198   176.3  4198.1   176.3    4338   175.1  4338.1   175.1    4358   174.6
  4358.1   174.6  4423.7  174.35    4438   174.3  4438.1   174.3    4478   173.5
  4478.1   173.5    4518   173.2  4518.1   173.2    4558   172.6  4558.1   172.6
    4688   170.9  4688.1   170.9    4698     171  4698.1     171    4748   170.2
  4748.1   170.2    4828   170.5  4828.1   170.5    4888     170  4888.1     170
  4908.1  170.08  4918.1  170.11 4922.73  170.13    4928  170.04  4948.1  169.69
    4958  169.52 4965.43  169.39  4968.1  169.43    4978  169.57 4981.13  169.62
 4981.43  166.81 4989.93  164.27 4990.04  164.23 4990.13  164.21 4994.93  162.77
 4995.43   162.3 4997.23  161.77 5000.23  161.57 5002.43  161.78 5004.63  162.33
 5006.93   165.3 5011.62  168.11 5011.73  168.17 5011.83  168.23 5015.33  170.33
    5018  170.35  5021.5  170.38 5026.23  170.42  5031.6  170.38  5041.6   170.3
 5042.63  170.29 5068.93  170.08  5201.5   169.5  5201.6   169.5  5261.5   168.4
  5261.6   168.4  5315.2  168.25  5331.5   168.2  5331.6   168.2  5341.5   168.3
  5341.6   168.3  5381.5   169.9  5381.6   169.9  5471.5   171.3  5471.6   171.3
  5561.5   171.7  5561.6   171.7  5601.5   171.7  5601.6   171.7  5681.5   173.1
  5681.6   173.1  5711.5     173  5711.6     173  5741.5   172.3  5741.6   172.3
  5751.5   172.2  5751.6   172.2  5761.5   172.5  5761.6   172.5  5861.5   171.6
  5861.6   171.6  5881.5     172  5881.6     172  5891.5   171.9  5891.6   171.9
  5901.5   171.5  5901.6   171.5  5931.5   171.2  5931.6   171.2  5941.5   171.3
  5941.6   171.3  5951.5   171.1  5951.6   171.1  5961.5   171.2  5961.6   171.2
  6001.5   171.1  6001.6   171.1  6091.5   169.9  6091.6   169.9  6131.5     170
  6131.6     170  6191.5     170  6191.6     170  6231.5   170.3  6231.6   170.3
  6281.5   169.8  6281.6   169.8  6301.5   169.8  6301.6   169.8  6321.5   169.6
  6321.6   169.6  6401.5   169.5  6401.6   169.5  6411.5   169.8  6411.6   169.8
  6431.5   170.7  6431.6   170.7  6451.5     171  6451.6     171  6471.5   170.8
  6471.6   170.8  6491.5   171.1  6491.6   171.1  6511.5   170.9  6511.6   170.9
  6574.2   172.1  6574.3   172.1  6574.4   172.1
BR U #Mann= 7
    4198      .2    4198     .05  4423.7     .08 4994.93    .045 5006.93     .15
  5315.2     .15  6574.2      .2
BR U Banks=4994.93,5006.93
BR D #Sta/Elev= 133
    4198   176.3  4198.1   176.3    4338   175.1  4338.1   175.1    4358   174.6
  4358.1   174.6  4423.7  174.35    4438   174.3  4438.1   174.3    4478   173.5
  4478.1   173.5    4518   173.2  4518.1   173.2    4558   172.6  4558.1   172.6
    4688   170.9  4688.1   170.9    4698     171  4698.1     171    4748   170.2
  4748.1   170.2    4828   170.5  4828.1   170.5    4888     170  4888.1     170
  4908.1  170.08  4918.1  170.11 4922.73  170.13    4928  170.04  4948.1  169.69
    4958  169.52 4965.43  169.39  4968.1  169.43    4978  169.57 4981.13  169.62
 4981.43  166.81 4989.93  164.27 4990.04  164.23 4990.13  164.21 4994.93  162.77
 4995.43   162.3 4997.23  161.77 5000.23  161.57 5002.43  161.78 5004.63  162.33
 5006.93   165.3 5011.62  168.11 5011.73  168.17 5011.83  168.23 5015.33  170.33
    5018  170.35  5021.5  170.38 5026.23  170.42  5031.6  170.38  5041.6   170.3
 5042.63  170.29 5068.93  170.08  5201.5   169.5  5201.6   169.5  5261.5   168.4
  5261.6   168.4  5315.2  168.25  5331.5   168.2  5331.6   168.2  5341.5   168.3
  5341.6   168.3  5381.5   169.9  5381.6   169.9  5471.5   171.3  5471.6   171.3
  5561.5   171.7  5561.6   171.7  5601.5   171.7  5601.6   171.7  5681.5   173.1
  5681.6   173.1  5711.5     173  5711.6     173  5741.5   172.3  5741.6   172.3
  5751.5   172.2  5751.6   172.2  5761.5   172.5  5761.6   172.5  5861.5   171.6
  5861.6   171.6  5881.5     172  5881.6     172  5891.5   171.9  5891.6   171.9
  5901.5   171.5  5901.6   171.5  5931.5   171.2  5931.6   171.2  5941.5   171.3
  5941.6   171.3  5951.5   171.1  5951.6   171.1  5961.5   171.2  5961.6   171.2
  6001.5   171.1  6001.6   171.1  6091.5   169.9  6091.6   169.9  6131.5     170
  6131.6     170  6191.5     170  6191.6     170  6231.5   170.3  6231.6   170.3
  6281.5   169.8  6281.6   169.8  6301.5   169.8  6301.6   169.8  6321.5   169.6
  6321.6   169.6  6401.5   169.5  6401.6   169.5  6411.5   169.8  6411.6   169.8
  6431.5   170.7  6431.6   170.7  6451.5     171  6451.6     171  6471.5   170.8
  6471.6   170.8  6491.5   171.1  6491.6   171.1  6511.5   170.9  6511.6   170.9
  6574.2   172.1  6574.3   172.1  6574.4   172.1
BR D #Mann= 7
    4198      .2    4198     .05  4423.7     .08 4994.93    .045 5006.93     .15
  5315.2     .15  6574.2      .2
BR D Banks=4994.93,5006.93
BC Design=,, 0 ,, 0 ,,,,,,
BC HTab HWMax=176.3

Type RM Length L Ch R = 1 ,8922.7  ,47.3,47.3,47.3
BEGIN DESCRIPTION:
Downstream Section of Bridge/Culvert/Weir
END DESCRIPTION:
XS GIS Cut Line= 4
      3029242.84      13954379.1      3028806.46      13953777.8
      3028784.75      13953673.9      3027665.41      13952641.1
#Sta/Elev= 30
    4198  176.17  4423.7  174.22    4748  170.07  4828.1  170.37 4981.13  169.49
 4981.43  166.68 4994.93  162.64 4997.23  161.64 5000.23  161.44 5004.63   162.2
 5006.93  165.17 5015.33   170.2  5201.6  169.37  5261.5  168.27  5315.2  168.12
  5341.6  168.17  5381.5  169.77  5471.5  171.17  5601.6  171.57  5681.5  172.97
  5751.5  172.07  5881.6  171.87  6001.6  170.97  6091.5  169.77  6231.6  170.17
  6401.5  169.37  6431.5  170.57  6511.6  170.77  6574.2  171.97  6574.4  171.97
#Mann= 7 , 1 , 0
    4198      .2       0    4198     .05       0  4423.7     .08       0
 4994.93     .07       0 5006.93     .15       0  5315.2     .15       0
  6574.2      .2       0
#XS Ineff= 2 , 0
       0                    6020       0   170.8
Permanent Ineff=
       F       F
Bank Sta=4994.93,5006.93
Exp/Cntr=0.5,0.3

Type RM Length L Ch R = 1 ,8875.4  ,34,34,34
BEGIN DESCRIPTION:
Upstream Section of Bridge/Culvert/Weir
END DESCRIPTION:
XS GIS Cut Line= 4
      3029361.45      13954330.5      3028908.52      13953811.8
      3028781.32      13953625.3      3027690.16      13952603.1
#Sta/Elev= 30
  4166.6  176.22  4341.2  174.88  4797.6  169.62  4857.6  170.22  4950.2     170
  4976.3  169.08  4981.1  166.45  4994.3  164.43  4995.2  162.33  4996.3  160.85
  4997.4  163.91  5000.4   161.1  5006.5  162.72  5009.6  164.16  5010.8  166.67
  5013.8  168.09  5015.5  170.07  5065.5  169.79    5265  169.18  5319.1  168.22
  5449.1  170.92  5719.1  172.92  5759.1  171.82  5809.1  172.82  5909.1  171.62
  6019.1  172.32  6139.1  169.92  6249.1  170.62  6419.1  169.72  6594.8  172.02
#Mann= 7 , 1 , 0
  4166.6      .2       0  4166.6     .05       0  4341.2     .08       0
  4994.3     .07       0  5006.5     .08       0  5065.5     .15       0
    5265     .15       0
#XS Ineff= 3 ,-1
  4166.6    4975  169.57 5013.17    6105   168.3  6105.1  6594.8   170.4
Permanent Ineff=
       F       F       F
Bank Sta=4994.3,5006.5
Exp/Cntr=0.5,0.3