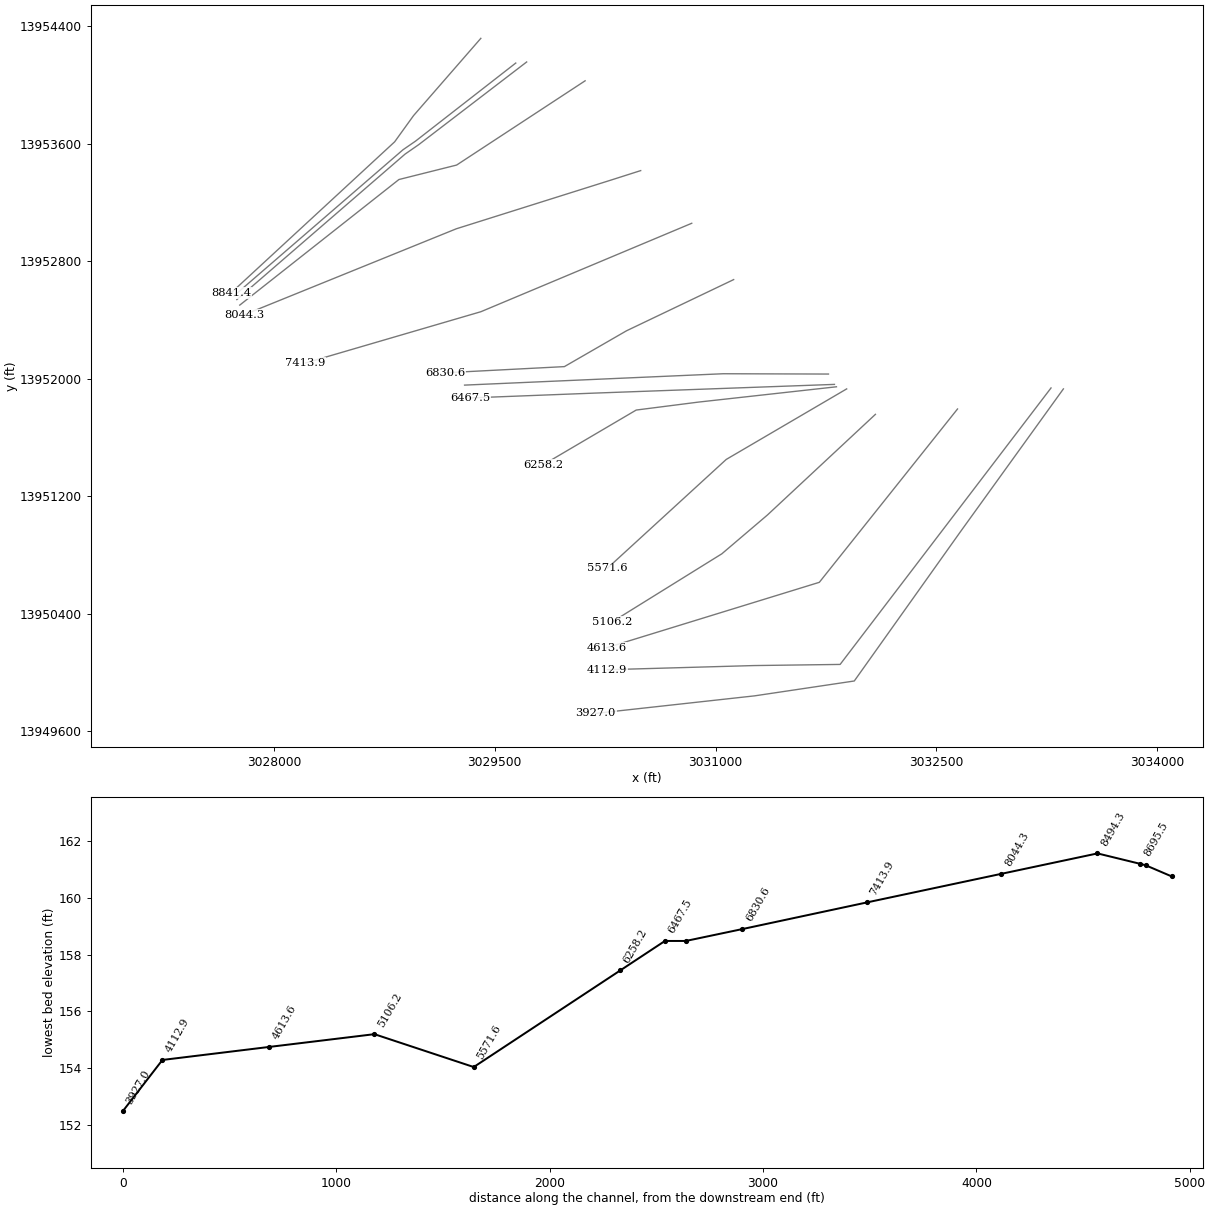
HEC-RAS study M124-00-00.PRJ: M124-00-00

--- M124-00-00.g01 (geometry) --- (continued)

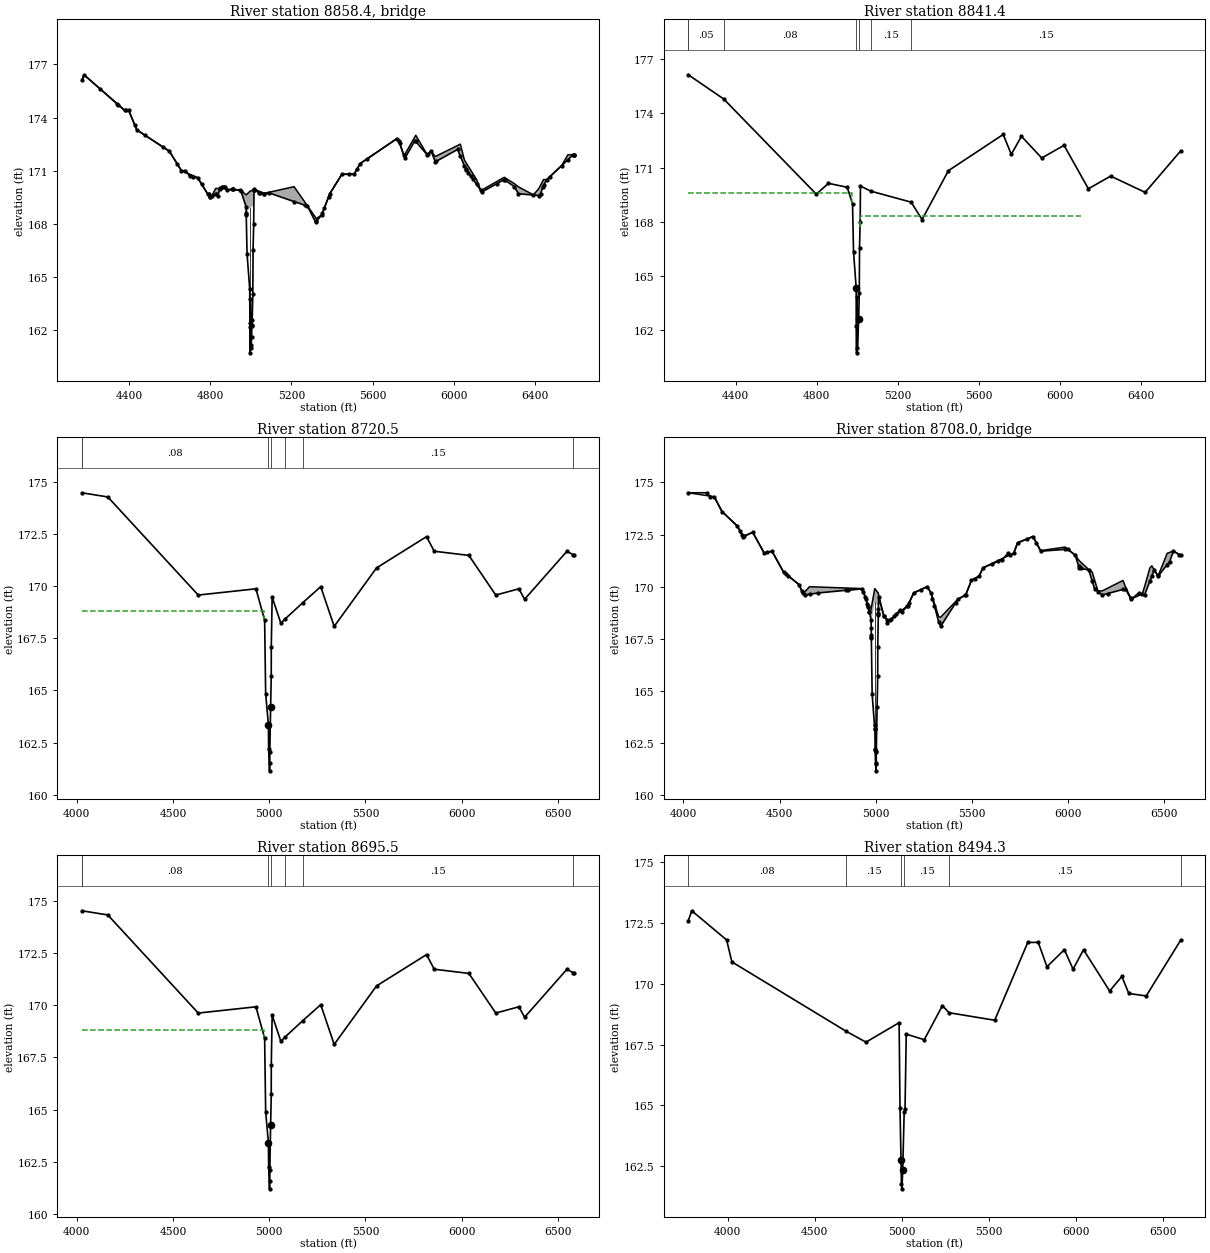
Type RM Length L Ch R = 3 ,8858.4  ,,,
BEGIN DESCRIPTION:
ACCESS ROAD 2ND US HUMBLE
Structure ID: M124-00-00-04
END DESCRIPTION:
Bridge Culvert--1,0,-1,-1, 0
Deck Dist Width WeirC Skew NumUp NumDn MinLoCord MaxHiCord MaxSubmerge Is_Ogee
10,14,2.6,0, 60, 60, , , 0.95, 0, 1,1,,
  4166.6  4177.6  4377.6  4397.6  4437.6  4597.6  4657.6  4737.6  4786.6  4797.6
  4806.6  4826.6  4837.6  4847.6  4857.6    4874  4879.9  4950.2  4976.3 4976.91
  4996.3  5013.8  5015.5  5065.5  5091.6  5212.9  5279.1  5319.1  5322.9  5349.1
  5389.1  5449.1  5509.1  5539.1  5719.1  5729.1  5752.9  5759.1  5809.1  5812.9
  5869.1  5889.1  5909.1  6019.1  6032.9  6052.9  6112.9  6132.9  6139.1  6249.1
  6299.1  6319.1  6392.9  6419.1  6429.1  6442.9  6459.1  6532.9  6562.9  6594.8
   176.1  176.41  174.41  174.41   173.3  172.11  171.01  170.61   169.7  169.75
  169.57     170     170  170.01  170.11  170.11  169.94  169.89  169.64  169.64
  169.85  169.92  169.96  169.73  169.79   170.1  169.02  168.36   168.3  168.51
  169.71  170.81  170.81  171.41  172.81  172.71  171.92  171.92  172.92     173
  171.91  172.11   171.8  172.42   172.5   171.6   170.5   169.9  169.91  170.63
  170.27  170.09  169.64  169.98   170.2   170.5   170.5   171.3   171.9   171.9
   176.1   176.4   174.4   174.4   173.3   172.1     171   170.6   169.7   169.5
  169.56  169.69   169.6     170   170.1   170.1  169.93  169.88  168.96  168.63
  168.95  169.02  169.95  169.67  169.74  169.26     169   168.1  168.15   168.5
   169.7   170.8   170.8   171.4   172.8   172.7  171.91   171.7   172.7  172.65
   171.9   172.1   171.5   172.2  171.82  171.27  170.23   169.9   169.8   170.5
   170.1   169.7  169.63   169.6   169.7  170.18   170.5  171.29  171.62   171.9
  4166.6  4177.6  4377.6  4397.6  4437.6  4597.6  4657.6  4737.6  4786.6  4797.6
  4806.6  4826.6  4837.6  4847.6  4857.6    4874  4879.9  4950.2  4976.3 4976.91
  4996.3  5013.8  5015.5  5065.5  5091.6  5212.9  5279.1  5319.1  5322.9  5349.1
  5389.1  5449.1  5509.1  5539.1  5719.1  5729.1  5752.9  5759.1  5809.1  5812.9
  5869.1  5889.1  5909.1  6019.1  6032.9  6052.9  6112.9  6132.9  6139.1  6249.1
  6299.1  6319.1  6392.9  6419.1  6429.1  6442.9  6459.1  6532.9  6562.9  6594.8
   176.1  176.41  174.41  174.41   173.3  172.11  171.01  170.61   169.7  169.75
  169.57     170     170  170.01  170.11  170.11  169.94  169.89  169.64  169.64
  169.85  169.92  169.96  169.73  169.79   170.1  169.02  168.36   168.3  168.51
  169.71  170.81  170.81  171.41  172.81  172.71  171.92  171.92  172.92     173
  171.91  172.11   171.8  172.42   172.5   171.6   170.5   169.9  169.91  170.63
  170.27  170.09  169.64  169.98   170.2   170.5   170.5   171.3   171.9   171.9
   176.1   176.4   174.4   174.4   173.3   172.1     171   170.6   169.7   169.5
  169.56  169.69   169.6     170   170.1   170.1  169.93  169.88  168.96  168.63
  168.95  169.02  169.95  169.67  169.74  169.26     169   168.1  168.15   168.5
   169.7   170.8   170.8   171.4   172.8   172.7  171.91   171.7   172.7  172.65
   171.9   172.1   171.5   172.2  171.82  171.27  170.23   169.9   169.8   170.5
   170.1   169.7  169.63   169.6   169.7  170.18   170.5  171.29  171.62   171.9
Pier Skew, UpSta & Num, DnSta & Num=  ,4997.4, 2 ,4997.4, 2 , 0 , 0 , 0 ,,
      .3      .3
  162.37  169.96
      .3      .3
  162.37  169.96
Abutment Skew #Up #Dn= , 2 , 2
  4976.8  4995.2
  168.74  162.21
  4976.8  4995.2
  168.74  162.21
Abutment Skew #Up #Dn= , 2 , 2
  5004.7 5016.89
  162.28  169.94
  5004.7 5016.89
  162.28  169.94
BR Coef= 1 , 1 , 1 ,0.95, 0 ,,,0.8,0,2,0,
WSPro=,,,, 1 ,,,, 0 ,,,, 0 ,,,,-1 ,-1 ,-1 , 0 , 0 , 0 , 0 , 0
BR U #Sta/Elev= 123
  4166.6   176.1  4177.6   176.4  4256.6  175.61  4341.2  174.76  4346.6  174.71
  4377.6   174.4  4386.6   174.4  4397.6   174.4  4426.6   173.6  4437.6   173.3
  4476.6  173.01  4566.6  172.33  4597.6   172.1  4636.6  171.39  4657.6     171
  4677.6     171  4697.6   170.7  4716.6  170.65  4737.6   170.6  4756.6  170.25
  4786.6   169.7  4796.6  169.52  4797.6   169.5  4806.6  169.56  4826.6  169.69
  4827.6   169.7  4837.6   169.6  4846.6  169.96  4847.6     170  4857.6   170.1
  4866.6   170.1    4874   170.1  4879.9  169.93  4906.6  169.95  4912.2  169.96
    4913  169.96  4947.2  169.89  4950.2  169.88  4976.3  168.96 4976.91  168.63
    4977  168.58  4977.1  168.52  4981.1  166.33  4994.3  164.31  4995.1  162.44
  4995.2  162.21  4996.3  160.73  4997.4  163.79  5000.4  160.98  5001.3  161.16
  5003.5   161.6  5004.6  162.22  5004.7  162.28  5006.5   162.6  5009.6  164.04
  5010.8  166.55  5013.8  167.97  5015.5  169.95 5016.69  169.94  5016.8  169.94
  5016.9  169.94  5042.4  169.72  5043.2  169.72  5065.3  169.67  5065.5  169.67
  5091.6  169.74  5212.9  169.26    5265  169.06  5279.1     169  5319.1   168.1
  5322.9  168.15  5349.1   168.5  5352.9  168.61  5362.9  168.91  5382.9  169.51
  5389.1   169.7  5449.1   170.8  5482.9   170.8  5509.1   170.8  5522.9  171.08
  5539.1   171.4  5572.9  171.66  5719.1   172.8  5729.1   172.7  5732.9  172.57
  5752.9  171.91  5759.1   171.7  5809.1   172.7  5812.9  172.65  5869.1   171.9
  5872.9  171.94  5889.1   172.1  5909.1   171.5  5912.9  171.52  6019.1   172.2
  6032.9  171.82  6052.9  171.27  6059.1   171.1  6062.9  171.04  6072.9  170.88
  6082.9  170.71  6092.9  170.55  6112.9  170.23  6132.9   169.9  6139.1   169.8
  6212.9  170.27  6249.1   170.5  6252.9  170.47  6299.1   170.1  6319.1   169.7
  6392.9  169.63  6419.1   169.6  6429.1   169.7  6439.1   170.1  6442.9  170.18
  6459.1   170.5  6472.9  170.65  6532.9  171.29  6562.9  171.62  6589.1   171.9
  6591.9   171.9  6594.7   171.9  6594.8   171.9
BR U #Mann= 6
  4166.6     .05  4341.2     .08  4994.3     .06  5006.5     .08  5065.5     .15
    5265     .15
BR U Banks=4994.3,5006.5
BR D #Sta/Elev= 123
  4166.6   176.1  4177.6   176.4  4256.6  175.61  4341.2  174.76  4346.6  174.71
  4377.6   174.4  4386.6   174.4  4397.6   174.4  4426.6   173.6  4437.6   173.3
  4476.6  173.01  4566.6  172.33  4597.6   172.1  4636.6  171.39  4657.6     171
  4677.6     171  4697.6   170.7  4716.6  170.65  4737.6   170.6  4756.6  170.25
  4786.6   169.7  4796.6  169.52  4797.6   169.5  4806.6  169.56  4826.6  169.69
  4827.6   169.7  4837.6   169.6  4846.6  169.96  4847.6     170  4857.6   170.1
  4866.6   170.1    4874   170.1  4879.9  169.93  4906.6  169.95  4912.2  169.96
    4913  169.96  4947.2  169.89  4950.2  169.88  4976.3  168.96 4976.91  168.63
    4977  168.58  4977.1  168.52  4981.1  166.33  4994.3  164.31  4995.1  162.44
  4995.2  162.21  4996.3  160.73  4997.4  163.79  5000.4  160.98  5001.3  161.16
  5003.5   161.6  5004.6  162.22  5004.7  162.28  5006.5   162.6  5009.6  164.04
  5010.8  166.55  5013.8  167.97  5015.5  169.95 5016.69  169.94  5016.8  169.94
  5016.9  169.94  5042.4  169.72  5043.2  169.72  5065.3  169.67  5065.5  169.67
  5091.6  169.74  5212.9  169.26    5265  169.06  5279.1     169  5319.1   168.1
  5322.9  168.15  5349.1   168.5  5352.9  168.61  5362.9  168.91  5382.9  169.51
  5389.1   169.7  5449.1   170.8  5482.9   170.8  5509.1   170.8  5522.9  171.08
  5539.1   171.4  5572.9  171.66  5719.1   172.8  5729.1   172.7  5732.9  172.57
  5752.9  171.91  5759.1   171.7  5809.1   172.7  5812.9  172.65  5869.1   171.9
  5872.9  171.94  5889.1   172.1  5909.1   171.5  5912.9  171.52  6019.1   172.2
  6032.9  171.82  6052.9  171.27  6059.1   171.1  6062.9  171.04  6072.9  170.88
  6082.9  170.71  6092.9  170.55  6112.9  170.23  6132.9   169.9  6139.1   169.8
  6212.9  170.27  6249.1   170.5  6252.9  170.47  6299.1   170.1  6319.1   169.7
  6392.9  169.63  6419.1   169.6  6429.1   169.7  6439.1   170.1  6442.9  170.18
  6459.1   170.5  6472.9  170.65  6532.9  171.29  6562.9  171.62  6589.1   171.9
  6591.9   171.9  6594.7   171.9  6594.8   171.9
BR D #Mann= 6
  4166.6     .05  4341.2     .08  4994.3     .06  5006.5     .08  5065.5     .15
    5265     .15
BR D Banks=4994.3,5006.5
BC Design=,, 0 ,, 0 ,,,,,,
BC HTab HWMax=176.52

Type RM Length L Ch R = 1 ,8841.4  ,120.9,120.9,120.9
BEGIN DESCRIPTION:
Downstream Section of Bridge/Culvert/Weir
END DESCRIPTION:
XS GIS Cut Line= 4
      3029405.24      13954316.6      3028948.25      13953790.8
      3028819.68      13953612.1      3027707.25      13952582.9
#Sta/Elev= 30
  4166.6  176.13  4341.2  174.79  4797.6  169.53  4857.6  170.13  4950.2  169.91
  4976.3  168.99  4981.1  166.36  4994.3  164.34  4995.2  162.24  4996.3  160.76
  4997.4  163.82  5000.4  161.01  5006.5  162.63  5009.6  164.07  5010.8  166.58
  5013.8     168  5015.5  169.98  5065.5   169.7    5265  169.09  5319.1  168.13
  5449.1  170.83  5719.1  172.83  5759.1  171.73  5809.1  172.73  5909.1  171.53
  6019.1  172.23  6139.1  169.83  6249.1  170.53  6419.1  169.63  6594.8  171.93
#Mann= 7 , 1 , 0
  4166.6      .2       0  4166.6     .05       0  4341.2     .08       0
  4994.3     .07       0  5006.5     .08       0  5065.5     .15       0
    5265     .15       0
#XS Ineff= 3 ,-1
  4166.6    4975  169.57 5013.17    6105   168.3  6105.1  6594.8   170.4
Permanent Ineff=
       F       F       F
Bank Sta=4994.3,5006.5
Exp/Cntr=0.5,0.3

Type RM Length L Ch R = 1 ,8720.5  ,25,25,25
BEGIN DESCRIPTION:
Upstream Section of Bridge/Culvert/Weir
END DESCRIPTION:
XS GIS Cut Line= 4
      3029642.61      13954148.4      3028961.88      13953617.1
      3028876.25       13953558.      3027727.85      13952563.7
#Sta/Elev= 30
  4025.9  174.47  4160.8  174.27  4630.8  169.57  4930.8  169.87    4976  168.37
  4981.4  164.84  4995.8  163.35  4996.8  162.19  5001.4  161.15  5002.9  161.53
    5003  162.05  5007.1  164.19  5010.4  165.67  5010.6  167.07  5015.1  169.47
  5060.3  168.22  5081.8  168.42  5174.8  169.21  5267.6  169.97  5337.6  168.07
  5557.6  170.87  5817.6  172.37  5857.6  171.67  6037.6  171.47  6177.6  169.57
  6297.6  169.87  6327.6  169.37  6547.6  171.67    6578  171.51  6585.9  171.47
#Mann= 7 , 1 , 0
  4025.9      .2       0  4025.9     .08       0  4995.8     .07       0
  5007.1     .08       0  5081.8     .15       0  5174.8     .15       0
    6578      .2       0
#XS Ineff= 3 ,-1
  4025.9    4975  168.82 5013.77    6110   168.4  6110.1  6585.9     170
Permanent Ineff=
       F       F       F
Bank Sta=4995.8,5007.1
Exp/Cntr=0.5,0.3

Type RM Length L Ch R = 3 ,8708.0  ,,,
BEGIN DESCRIPTION:
FOOT BRIDGE US HUMBLE RD
Structure ID: M124-00-00-03
END DESCRIPTION:
Bridge Culvert--1,0,-1,-1, 0
Deck Dist Width WeirC Skew NumUp NumDn MinLoCord MaxHiCord MaxSubmerge Is_Ogee
10,5,2.6,0, 60, 60, , , 0.95, 0, 1,1,,
  4025.9  4160.8  4200.8  4280.8  4310.8  4360.8  4420.8  4460.8  4520.8  4600.8
  4620.8  4630.8  4655.9  4930.8  4967.1    4976 4977.21  4977.3  4995.2 5013.49
  5013.6  5015.1  5042.2  5060.3  5075.2  5167.6  5197.6  5267.6  5287.6  5327.6
  5337.6  5427.6  5467.6  5497.6  5537.6  5557.6  5717.6  5737.6  5817.6  5857.6
  5985.2  6037.6  6057.6  6107.6  6125.2  6137.6  6155.2  6177.6  6285.2  6297.6
  6327.6  6385.2  6397.6  6425.2  6435.2  6447.6  6467.6  6515.2  6547.6  6585.9
   174.5  174.31  173.61  172.91  172.41  172.61  171.61  171.71  170.71  170.11
  169.71  169.75     170  169.91  168.82   168.9     169     169  169.91  169.69
  169.69  169.59  168.61  168.41   168.4  169.11  169.71  170.01  169.71  168.56
  168.54  169.41  169.61  170.31  170.51  170.91  171.61  172.11  172.41  171.73
   171.9  171.51  171.25  170.82   170.7  170.33   169.8   169.8   170.3  170.02
  169.41  169.65     170   170.9     171  170.81  170.51   171.6  171.71   171.5
   174.5   174.3   173.6   172.9   172.4   172.6   171.6   171.7   170.7   170.1
   169.7   169.6  169.64   169.9  168.81   168.4  167.61  168.35  169.26  169.04
   168.7   169.5   168.6  168.25  168.39   169.1   169.7     170   169.7   168.3
   168.1   169.4   169.6   170.3   170.5   170.9   171.6   172.1   172.4   171.7
  171.79   171.5   170.9   170.8  170.27   169.9  169.77   169.6  169.87   169.9
   169.4  169.64   169.6  170.26   170.5   170.8   170.5  171.06   171.7   171.5
  4025.9  4160.8  4200.8  4280.8  4310.8  4360.8  4420.8  4460.8  4520.8  4600.8
  4620.8  4630.8  4655.9  4930.8  4967.1    4976 4977.21  4977.3  4995.2 5013.49
  5013.6  5015.1  5042.2  5060.3  5075.2  5167.6  5197.6  5267.6  5287.6  5327.6
  5337.6  5427.6  5467.6  5497.6  5537.6  5557.6  5717.6  5737.6  5817.6  5857.6
  5985.2  6037.6  6057.6  6107.6  6125.2  6137.6  6155.2  6177.6  6285.2  6297.6
  6327.6  6385.2  6397.6  6425.2  6435.2  6447.6  6467.6  6515.2  6547.6  6585.9
   174.5  174.31  173.61  172.91  172.41  172.61  171.61  171.71  170.71  170.11
  169.71  169.75     170  169.91  168.82   168.9     169     169  169.91  169.69
  169.69  169.59  168.61  168.41   168.4  169.11  169.71  170.01  169.71  168.56
  168.54  169.41  169.61  170.31  170.51  170.91  171.61  172.11  172.41  171.73
   171.9  171.51  171.25  170.82   170.7  170.33   169.8   169.8   170.3  170.02
  169.41  169.65     170   170.9     171  170.81  170.51   171.6  171.71   171.5
   174.5   174.3   173.6   172.9   172.4   172.6   171.6   171.7   170.7   170.1
   169.7   169.6  169.64   169.9  168.81   168.4  167.61  168.35  169.26  169.04
   168.7   169.5   168.6  168.25  168.39   169.1   169.7     170   169.7   168.3
   168.1   169.4   169.6   170.3   170.5   170.9   171.6   172.1   172.4   171.7
  171.79   171.5   170.9   170.8  170.27   169.9  169.77   169.6  169.87   169.9
   169.4  169.64   169.6  170.26   170.5   170.8   170.5  171.06   171.7   171.5
Pier Skew, UpSta & Num, DnSta & Num=  ,4995.2, 2 ,4995.2, 2 , 0 , 0 , 0 ,,
      .5      .5
  162.19  170.26
      .5      .5
  162.19  170.26
Abutment Skew #Up #Dn= , 2 , 2
  4977.1  4996.9
  168.35  162.19
  4977.1  4996.9
  168.35  162.19
Abutment Skew #Up #Dn= , 2 , 2
  5003.1 5013.69
  162.13  169.04
  5003.1 5013.69
  162.13  169.04
BR Coef= 1 , 1 , 1 ,0.95, 0 ,,,0.8,0,2,0,
WSPro=,,,, 1 ,,,, 0 ,,,, 0 ,,,,-1 ,-1 ,-1 , 0 , 0 , 0 , 0 , 0
BR U #Sta/Elev= 127
  4025.9   174.5  4120.8   174.5  4140.8   174.3  4160.8   174.3  4200.8   173.6
  4280.8   172.9  4295.9  172.65  4305.9  172.48  4310.8   172.4  4315.9  172.42
  4360.8   172.6  4420.8   171.6  4435.9  171.64  4460.8   171.7  4520.8   170.7
  4535.9  170.59  4545.9  170.51  4600.8   170.1  4615.9   169.8  4620.8   169.7
  4630.8   169.6  4655.9  169.64  4700.8   169.7  4845.9  169.83  4855.9  169.83
  4930.8   169.9  4935.9  169.77  4945.9  169.52  4950.8   169.4  4955.9  169.18
  4958.2  169.08  4958.4  169.02  4967.1  168.81  4967.7  168.78    4976   168.4
  4976.6  168.01  4977.1  167.68 4977.21  167.61  4977.3  167.55  4981.4  164.87
  4995.1  163.17  4995.2   163.2  4995.8  163.38  4996.8  162.22  4996.9  162.19
  4999.2  161.53  5001.4  161.18  5002.9  161.56    5003  162.08  5003.1  162.13
  5007.1  164.22  5010.4   165.7  5010.6   167.1 5013.49  168.64  5013.6   168.7
  5013.7  168.75    5014  168.91  5015.1   169.5  5042.2   168.6  5044.1  168.58
  5057.9  168.42  5060.3  168.25  5075.2  168.39  5081.8  168.45  5097.6   168.6
  5105.2  168.68  5127.6   168.9  5137.6   168.8  5165.2  169.08  5167.6   169.1
  5174.8  169.24  5197.6   169.7  5235.2  169.86  5267.6     170  5287.6   169.7
  5295.2  169.43  5305.2  169.08  5327.6   168.3  5337.6   168.1  5415.2  169.22
  5427.6   169.4  5465.2  169.59  5467.6   169.6  5497.6   170.3  5515.2  170.39
  5537.6   170.5  5557.6   170.9  5605.2  171.09  5635.2  171.21  5657.6   171.3
  5687.6   171.6  5697.6   171.5  5717.6   171.6  5737.6   172.1  5785.2  172.28
  5817.6   172.4  5835.2  172.09  5857.6   171.7  5985.2  171.79  5997.6   171.8
  6037.6   171.5  6055.2  170.97  6057.6   170.9  6065.2  170.88  6107.6   170.8
  6125.2  170.27  6137.6   169.9  6155.2  169.77  6177.6   169.6  6205.2  169.67
  6285.2  169.87  6297.6   169.9  6325.2  169.44  6327.6   169.4  6367.6   169.7
  6385.2  169.64  6397.6   169.6  6425.2  170.26  6435.2   170.5  6447.6   170.8
  6465.2  170.54  6467.6   170.5  6515.2  171.06  6527.6   171.2  6547.6   171.7
    6578  171.54  6585.9   171.5
BR U #Mann= 6
  4025.9     .08  4995.8     .06  5007.1     .08  5081.8     .15  5174.8     .15
    6578      .2
BR U Banks=4995.8,5007.1
BR D #Sta/Elev= 127
  4025.9   174.5  4120.8   174.5  4140.8   174.3  4160.8   174.3  4200.8   173.6
  4280.8   172.9  4295.9  172.65  4305.9  172.48  4310.8   172.4  4315.9  172.42
  4360.8   172.6  4420.8   171.6  4435.9  171.64  4460.8   171.7  4520.8   170.7
  4535.9  170.59  4545.9  170.51  4600.8   170.1  4615.9   169.8  4620.8   169.7
  4630.8   169.6  4655.9  169.64  4700.8   169.7  4845.9  169.83  4855.9  169.83
  4930.8   169.9  4935.9  169.77  4945.9  169.52  4950.8   169.4  4955.9  169.18
  4958.2  169.08  4958.4  169.02  4967.1  168.81  4967.7  168.78    4976   168.4
  4976.6  168.01  4977.1  167.68 4977.21  167.61  4977.3  167.55  4981.4  164.87
  4995.1  163.17  4995.2   163.2  4995.8  163.38  4996.8  162.22  4996.9  162.19
  4999.2  161.53  5001.4  161.18  5002.9  161.56    5003  162.08  5003.1  162.13
  5007.1  164.22  5010.4   165.7  5010.6   167.1 5013.49  168.64  5013.6   168.7
  5013.7  168.75    5014  168.91  5015.1   169.5  5042.2   168.6  5044.1  168.58
  5057.9  168.42  5060.3  168.25  5075.2  168.39  5081.8  168.45  5097.6   168.6
  5105.2  168.68  5127.6   168.9  5137.6   168.8  5165.2  169.08  5167.6   169.1
  5174.8  169.24  5197.6   169.7  5235.2  169.86  5267.6     170  5287.6   169.7
  5295.2  169.43  5305.2  169.08  5327.6   168.3  5337.6   168.1  5415.2  169.22
  5427.6   169.4  5465.2  169.59  5467.6   169.6  5497.6   170.3  5515.2  170.39
  5537.6   170.5  5557.6   170.9  5605.2  171.09  5635.2  171.21  5657.6   171.3
  5687.6   171.6  5697.6   171.5  5717.6   171.6  5737.6   172.1  5785.2  172.28
  5817.6   172.4  5835.2  172.09  5857.6   171.7  5985.2  171.79  5997.6   171.8
  6037.6   171.5  6055.2  170.97  6057.6   170.9  6065.2  170.88  6107.6   170.8
  6125.2  170.27  6137.6   169.9  6155.2  169.77  6177.6   169.6  6205.2  169.67
  6285.2  169.87  6297.6   169.9  6325.2  169.44  6327.6   169.4  6367.6   169.7
  6385.2  169.64  6397.6   169.6  6425.2  170.26  6435.2   170.5  6447.6   170.8
  6465.2  170.54  6467.6   170.5  6515.2  171.06  6527.6   171.2  6547.6   171.7
    6578  171.54  6585.9   171.5
BR D #Mann= 6
  4025.9     .08  4995.8     .06  5007.1     .08  5081.8     .15  5174.8     .15
    6578      .2
BR D Banks=4995.8,5007.1
BC Design=,, 0 ,, 0 ,,,,,,
BC HTab HWMax=174.47

Type RM Length L Ch R = 1 ,8695.5  ,201.2,201.2,201.2
BEGIN DESCRIPTION:
Downstream Section of Bridge/Culvert/Weir
END DESCRIPTION:
XS GIS Cut Line= 4
      3029716.62      13954155.7      3028983.15      13953592.9
      3028890.45      13953528.5      3027747.56      13952538.4
#Sta/Elev= 30
  4025.9  174.52  4160.8  174.32  4630.8  169.62  4930.8  169.92    4976  168.42
  4981.4  164.89  4995.8   163.4  4996.8  162.24  5001.4   161.2  5002.9  161.58
    5003   162.1  5007.1  164.24  5010.4  165.72  5010.6  167.12  5015.1  169.52
  5060.3  168.27  5081.8  168.47  5174.8  169.26  5267.6  170.02  5337.6  168.12
  5557.6  170.92  5817.6  172.42  5857.6  171.72  6037.6  171.52  6177.6  169.62
  6297.6  169.92  6327.6  169.42  6547.6  171.72    6578  171.56  6585.9  171.52
#Mann= 7 , 1 , 0
  4025.9      .2       0  4025.9     .08       0  4995.8     .07       0
  5007.1     .08       0  5081.8     .15       0  5174.8     .15       0
    6578      .2       0
#XS Ineff= 3 ,-1
  4025.9    4975  168.82 5013.77    6110   168.4  6110.1  6585.9     170
Permanent Ineff=
       F       F       F
Bank Sta=4995.8,5007.1
Exp/Cntr=0.5,0.3

Type RM Length L Ch R = 1 ,8494.3  ,484.54,450,434.1
BEGIN DESCRIPTION:
Cross Section XS-03
END DESCRIPTION:
XS GIS Cut Line= 4
      3030113.85      13954027.5      3029240.79       13953454.
      3028848.67      13953355.5      3027767.29      13952500.7
#Sta/Elev= 30
  3773.8   172.6  3793.8     173  3993.8   171.8  4023.8   170.9    4679  168.05
  4793.8   167.6    4984   168.4    4989   164.9  4994.9  162.77  4997.2  161.77
  5000.2  161.57  5004.6  162.33    5013  164.72    5018  164.87    5025  167.93
  5128.4   167.7  5232.7   169.1  5270.4  168.81 5532.71   168.5  5722.7   171.7
  5782.7   171.7  5832.7   170.7  5932.7   171.4  5982.7   170.6  6042.7   171.4
  6192.7   169.7  6262.7   170.3  6302.7   169.6  6402.7   169.5  6601.1   171.8
#Mann= 6 ,-1 , 0
  3773.8     .08       0    4679     .15       0  4994.9     .07       0
    5013     .15       0  5270.4     .15       0  6601.1      .2       0
Bank Sta=4994.9,5004.6
Exp/Cntr=0.3,0.1

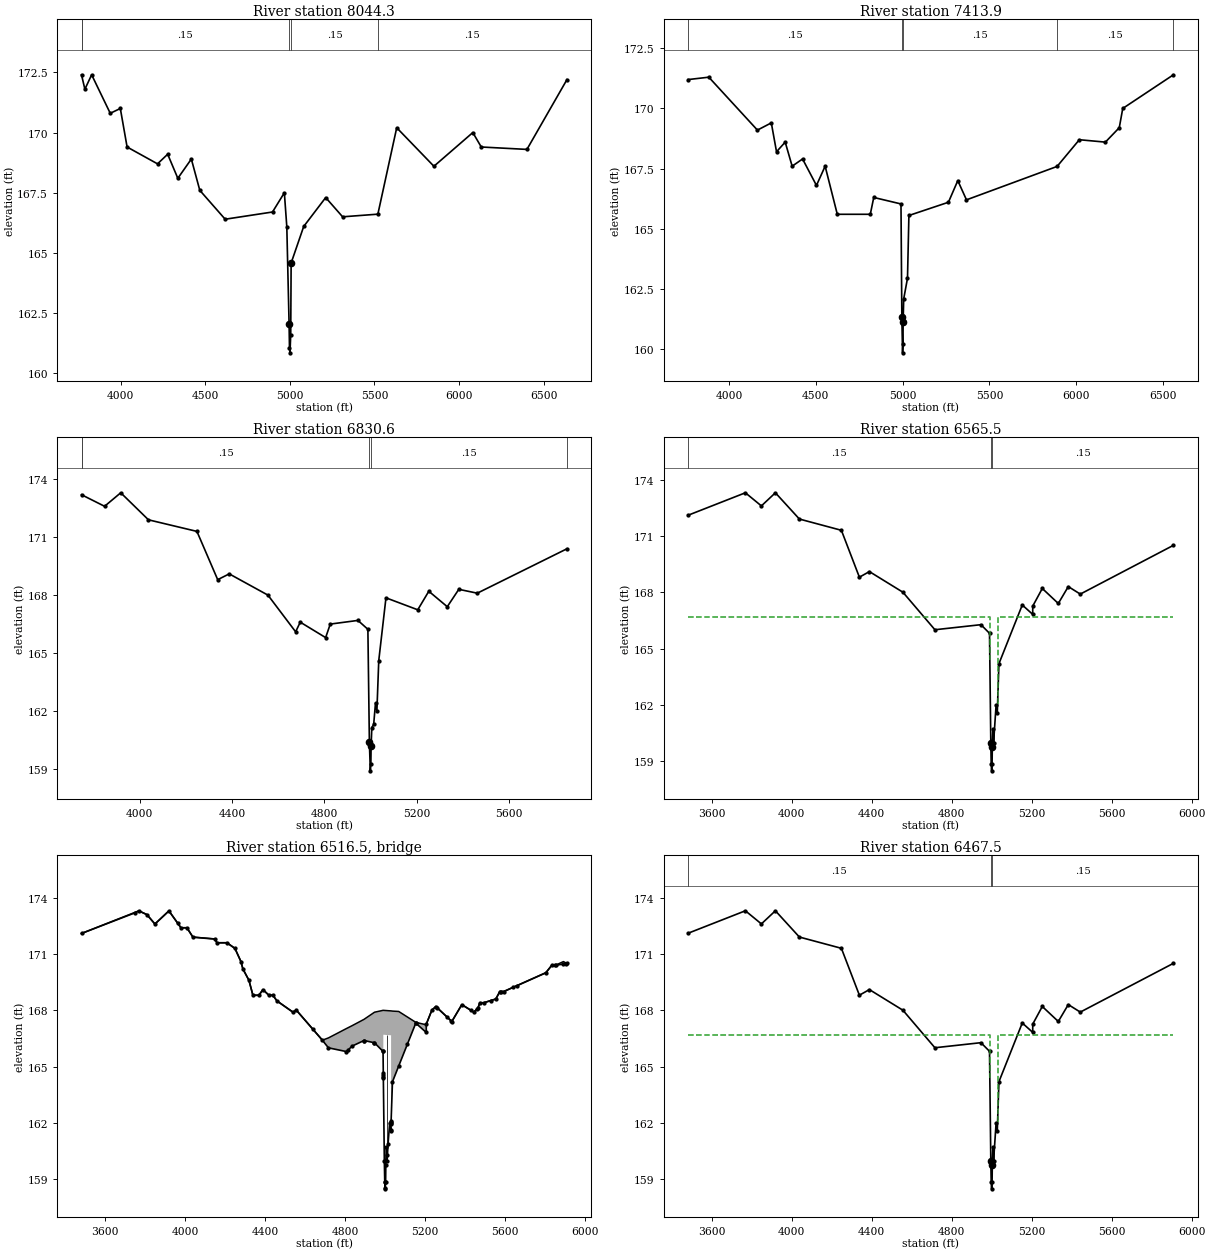
Type RM Length L Ch R = 1 ,8044.3  ,556.7,630.4,657.96
BEGIN DESCRIPTION:
Cross Section XS-02.9
END DESCRIPTION:
XS GIS Cut Line= 4
      3030491.33      13953416.2      3030291.67      13953352.4
      3029238.36      13953020.1        3027796.      13952434.3
#Sta/Elev= 30
  3767.3   172.4  3787.3   171.8  3827.3   172.4  3937.3   170.8  3996.9     171
  4036.9   169.4  4216.9   168.7  4276.9   169.1  4336.9   168.1  4416.9   168.9
  4466.9   167.6  4616.9   166.4  4896.9   166.7  4966.9   167.5  4981.4  166.09
  4994.9  162.05  4997.2  161.05  5000.2  160.85  5004.6  161.61    5007  164.58
  5081.4   166.1  5211.4   167.3  5311.4   166.5  5519.9  166.61  5631.4   170.2
  5851.4   168.6  6081.4     170  6131.4   169.4  6401.4   169.3  6638.2   172.2
#Mann= 5 , 1 , 0
  3767.3      .2       0  3767.3     .15       0  4994.9     .07       0
    5007     .15       0  5519.9     .15       0
Bank Sta=4994.9,5007
Exp/Cntr=0.3,0.1

Type RM Length L Ch R = 1 ,7413.9  ,536.84,583.3,609.98
BEGIN DESCRIPTION:
Cross Section XS02.8
END DESCRIPTION:
XS GIS Cut Line= 3
      3030838.26      13953057.7      3029405.61      13952455.7
      3028213.75      13952106.6
#Sta/Elev= 30
    3764   171.2    3884   171.3    4164   169.1    4244   169.4    4274   168.2
    4324   168.6    4364   167.6    4424   167.9    4504   166.8    4554   167.6
    4624   165.6    4814   165.6    4834   166.3  4990.8  166.03  4995.8  161.31
  4999.9  159.84  5002.2  160.21  5003.2  161.12  5006.4  162.08  5028.3  162.94
  5036.4  165.55    5264   166.1    5318     167    5368   166.2  5889.9  167.59
    6018   168.7    6168   168.6    6248   169.2    6268     170  6559.9   171.4
#Mann= 5 ,-1 , 0
    3764     .15       0  4995.8     .07       0  5003.2     .15       0
  5889.9     .15       0  6559.9      .2       0
Bank Sta=4995.8,5003.2
Exp/Cntr=0.3,0.1

Type RM Length L Ch R = 1 ,6830.6  ,252.84,265.1,143.83
BEGIN DESCRIPTION:
Cross Section XS-02.7-Bridge1-con
END DESCRIPTION:
XS GIS Cut Line= 4
      3031123.02      13952674.3       3030394.6      13952325.6
      3029972.99       13952082.      3029165.59      13952040.1
#Sta/Elev= 30
  3748.7   173.2  3848.7   172.6  3918.7   173.3  4038.7   171.9  4248.7   171.3
  4338.7   168.8  4388.7   169.1  4556.3     168  4676.3   166.1  4696.3   166.6
  4806.3   165.8  4826.3   166.5  4946.2  166.69  4989.3  166.23  4995.8  160.37
  4999.9   158.9  5002.2  159.27  5003.2  160.18  5006.4  161.14  5014.4   161.3
  5022.3  162.42  5028.3     162  5036.4  164.61  5067.6  167.86  5205.3  167.24
  5253.2   168.2  5333.2   167.4  5383.2   168.3  5463.2   168.1  5851.7   170.4
#Mann= 5 , 1 , 0
  3748.7      .2       0  3748.7     .15       0  4995.8     .07       0
  5003.2     .15       0  5851.7      .2       0
Bank Sta=4995.8,5003.2
Exp/Cntr=0.5,0.3

Type RM Length L Ch R = 1 ,6565.5  ,98,98,98
BEGIN DESCRIPTION:
Upstream Section of Bridge/Culvert/Weir
END DESCRIPTION:
XS GIS Cut Line= 3
      3031767.31      13952031.4       3031051.7      13952033.5
      3029294.76      13951956.1
#Sta/Elev= 30
  3481.6   172.1  3768.7   173.3  3848.7   172.6  3918.7   173.3  4038.7   171.9
  4248.7   171.3  4338.7   168.8  4388.7   169.1  4556.3     168  4716.3     166
  4946.5  166.27  4989.3  165.81  4995.8  159.95  4997.8  158.83  4999.9  158.48
  5002.2  158.85  5003.2  159.76  5006.4  160.72  5009.7  159.98  5022.3     162
  5028.2  161.58  5036.4  164.19  5153.1  167.32  5205.3  166.82  5205.5  167.26
  5253.2   168.2  5333.2   167.4  5383.2   168.3  5443.2   167.9  5908.9   170.5
#Mann= 3 , 1 , 0
  3481.6     .15       0  4995.8     .07       0  5003.2     .15       0
#XS Ineff= 2 , 0
       0  4990.9   166.7  5029.6       0   166.7
Permanent Ineff=
       F       F
Bank Sta=4995.8,5003.2
Exp/Cntr=0.5,0.3

Type RM Length L Ch R = 3 ,6516.5  ,,,
BEGIN DESCRIPTION:
HUMBLE ROAD
Structure ID: M124-00-00-02
END DESCRIPTION:
Bridge Culvert--1,0,-1,-1, 0
Deck Dist Width WeirC Skew NumUp NumDn MinLoCord MaxHiCord MaxSubmerge Is_Ogee
10,78,2.6,0, 55, 55, , , 0.95, 0, 1,1,,
  3481.6  3768.7  3808.7  3848.7  3918.7  3978.7  4008.7  4038.7  4148.7  4158.7
  4208.7  4248.7  4278.7  4288.7  4318.7  4338.7  4368.7  4388.7  4418.7  4438.7
  4458.7  4538.7  4556.3  4686.3  4716.3  4806.3  4834.1  4894.2  4946.5  4989.3
 4990.73  4990.8 5029.49  5029.6  5036.4  5067.6  5153.1  5205.3  5205.5  5233.2
  5253.2  5333.2  5383.2  5443.2  5463.2  5473.2  5493.2  5553.2  5573.2  5593.2
  5803.2  5833.2  5851.7  5891.3  5908.9
   172.1  173.31  173.11  172.61  173.31  172.41  172.41  171.91  171.81  171.61
  171.61  171.31  170.61  170.21  169.61  168.81  168.81  169.11  168.81  168.81
  168.51  167.91  168.01  166.41  166.53  167.03  167.18  167.52   167.9     168
     168     168  167.97  167.97  167.96  167.94  167.36  167.23  167.27  168.01
  168.21  167.41  168.31  167.91  168.11  168.41  168.41  168.61  169.01  169.01
  170.01  170.41  170.41   170.6   170.5
   172.1   173.3   173.1   172.6   173.3   172.4   172.4   171.9   171.8   171.6
   171.6   171.3   170.6   170.2   169.6   168.8   168.8   169.1   168.8   168.8
   168.5   167.9     168   166.4     166   165.8  166.09  166.39  166.27  165.81
  164.47   166.7  166.67  162.08  164.19  165.03  167.32  166.82  167.26     168
   168.2   167.4   168.3   167.9   168.1   168.4   168.4   168.6     169     169
     170   170.4   170.4  170.47   170.5
  3481.6  3768.7  3808.7  3848.7  3918.7  3978.7  4008.7  4038.7  4148.7  4158.7
  4208.7  4248.7  4278.7  4288.7  4318.7  4338.7  4368.7  4388.7  4418.7  4438.7
  4458.7  4538.7  4556.3  4686.3  4716.3  4806.3  4834.1  4894.2  4946.5  4989.3
 4990.73  4990.8 5029.49  5029.6  5036.4  5067.6  5153.1  5205.3  5205.5  5233.2
  5253.2  5333.2  5383.2  5443.2  5463.2  5473.2  5493.2  5553.2  5573.2  5593.2
  5803.2  5833.2  5851.7  5891.3  5908.9
   172.1  173.31  173.11  172.61  173.31  172.41  172.41  171.91  171.81  171.61
  171.61  171.31  170.61  170.21  169.61  168.81  168.81  169.11  168.81  168.81
  168.51  167.91  168.01  166.41  166.53  167.03  167.18  167.52   167.9     168
     168     168  167.97  167.97  167.96  167.94  167.36  167.23  167.27  168.01
  168.21  167.41  168.31  167.91  168.11  168.41  168.41  168.61  169.01  169.01
  170.01  170.41  170.41   170.6   170.5
   172.1   173.3   173.1   172.6   173.3   172.4   172.4   171.9   171.8   171.6
   171.6   171.3   170.6   170.2   169.6   168.8   168.8   169.1   168.8   168.8
   168.5   167.9     168   166.4     166   165.8  166.09  166.39  166.27  165.81
  164.47   166.7  166.67  162.08  164.19  165.03  167.32  166.82  167.26     168
   168.2   167.4   168.3   167.9   168.1   168.4   168.4   168.6     169     169
     170   170.4   170.4  170.47   170.5
Pier Skew, UpSta & Num, DnSta & Num=  ,5009.9, 2 ,5009.9, 2 , 0 , 0 , 0 ,,
       1       1
  159.05  167.73
       1       1
  159.05  167.73
Abutment Skew #Up #Dn= , 2 , 2
  5028.3 5029.69
  161.62  166.67
  5028.3 5029.69
  161.62  166.67
BR Coef= 1 , 1 , 1 ,1.25, 0 ,,,0.8,-1,2,0,
WSPro=,,,, 1 ,,,, 0 ,,,, 0 ,,,,-1 ,-1 ,-1 , 0 , 0 , 0 , 0 , 0
BR U #Sta/Elev= 93
  3481.6   172.1  3748.7   173.2  3768.7   173.3  3808.7   173.1  3848.7   172.6
  3918.7   173.3  3961.6  172.66  3978.7   172.4  4008.7   172.4  4038.7   171.9
  4148.7   171.8  4158.7   171.6  4208.7   171.6  4248.7   171.3  4278.7   170.6
  4288.7   170.2  4318.7   169.6  4338.7   168.8  4368.7   168.8  4388.7   169.1
  4418.7   168.8  4438.7   168.8  4458.7   168.5  4538.7   167.9  4556.3     168
  4638.4  166.99  4686.3   166.4  4716.3     166  4806.3   165.8  4816.3   165.9
  4834.1  166.09  4894.2  166.39  4894.9  166.39  4946.2  166.27  4946.5  166.27
  4987.3  165.83  4989.3  165.81  4990.5  164.67 4990.61  164.57 4990.73  164.47
  4990.8   164.4  4995.8  159.95  4997.8  158.83  4998.3  158.83  4999.8   158.5
  4999.9  158.48  5002.2  158.85  5003.2  159.76  5006.4  160.72  5009.7  159.98
  5011.2  160.27  5014.4  160.88  5022.3     162  5028.2  161.58  5028.3  161.62
  5029.1  161.92  5029.4  162.01 5029.49  162.04  5029.6  162.08  5036.4  164.19
  5067.6  165.03  5111.2   166.2  5153.1  167.32  5153.7  167.31  5205.3  166.82
  5205.5  167.26  5233.2     168  5253.2   168.2  5258.4  168.15  5308.4  167.65
  5328.4  167.45  5333.2   167.4  5383.2   168.3  5428.4     168  5443.2   167.9
  5458.4  168.05  5463.2   168.1  5473.2   168.4  5493.2   168.4  5528.4  168.52
  5553.2   168.6  5573.2     169  5578.4     169  5593.2     169  5638.4  169.22
  5658.4  169.31  5803.2     170  5833.2   170.4  5848.4   170.4  5851.7   170.4
  5891.3  170.47  5903.1  170.49  5908.9   170.5
BR U #Mann= 3
  3481.6     .15  4995.8     .06  5003.2     .15
BR U Banks=4995.8,5003.2
BR D #Sta/Elev= 93
  3481.6   172.1  3748.7   173.2  3768.7   173.3  3808.7   173.1  3848.7   172.6
  3918.7   173.3  3961.6  172.66  3978.7   172.4  4008.7   172.4  4038.7   171.9
  4148.7   171.8  4158.7   171.6  4208.7   171.6  4248.7   171.3  4278.7   170.6
  4288.7   170.2  4318.7   169.6  4338.7   168.8  4368.7   168.8  4388.7   169.1
  4418.7   168.8  4438.7   168.8  4458.7   168.5  4538.7   167.9  4556.3     168
  4638.4  166.99  4686.3   166.4  4716.3     166  4806.3   165.8  4816.3   165.9
  4834.1  166.09  4894.2  166.39  4894.9  166.39  4946.2  166.27  4946.5  166.27
  4987.3  165.83  4989.3  165.81  4990.5  164.67 4990.61  164.57 4990.73  164.47
  4990.8   164.4  4995.8  159.95  4997.8  158.83  4998.3  158.83  4999.8   158.5
  4999.9  158.48  5002.2  158.85  5003.2  159.76  5006.4  160.72  5009.7  159.98
  5011.2  160.27  5014.4  160.88  5022.3     162  5028.2  161.58  5028.3  161.62
  5029.1  161.92  5029.4  162.01 5029.49  162.04  5029.6  162.08  5036.4  164.19
  5067.6  165.03  5111.2   166.2  5153.1  167.32  5153.7  167.31  5205.3  166.82
  5205.5  167.26  5233.2     168  5253.2   168.2  5258.4  168.15  5308.4  167.65
  5328.4  167.45  5333.2   167.4  5383.2   168.3  5428.4     168  5443.2   167.9
  5458.4  168.05  5463.2   168.1  5473.2   168.4  5493.2   168.4  5528.4  168.52
  5553.2   168.6  5573.2     169  5578.4     169  5593.2     169  5638.4  169.22
  5658.4  169.31  5803.2     170  5833.2   170.4  5848.4   170.4  5851.7   170.4
  5891.3  170.47  5903.1  170.49  5908.9   170.5
BR D #Mann= 3
  3481.6     .15  4995.8     .06  5003.2     .15
BR D Banks=4995.8,5003.2
BC Design=,, 0 ,, 0 ,,,,,,
BC HTab HWMax=173.3

Type RM Length L Ch R = 1 ,6467.5  ,209.3,209.3,209.3
BEGIN DESCRIPTION:
Downstream Section of Bridge/Culvert/Weir
END DESCRIPTION:
XS GIS Cut Line= 3
      3031807.93       13951961.      3030183.64      13951901.9
      3029331.87      13951868.8
#Sta/Elev= 30
  3481.6   172.1  3768.7   173.3  3848.7   172.6  3918.7   173.3  4038.7   171.9
  4248.7   171.3  4338.7   168.8  4388.7   169.1  4556.3     168  4716.3     166
  4946.5  166.27  4989.3  165.81  4995.8  159.95  4997.8  158.83  4999.9  158.48
  5002.2  158.85  5003.2  159.76  5006.4  160.72  5009.7  159.98  5022.3     162
  5028.2  161.58  5036.4  164.19  5153.1  167.32  5205.3  166.82  5205.5  167.26
  5253.2   168.2  5333.2   167.4  5383.2   168.3  5443.2   167.9  5908.9   170.5
#Mann= 3 , 1 , 0
  3481.6     .15       0  4995.8     .07       0  5003.2     .15       0
#XS Ineff= 2 , 0
       0  4990.9   166.7  5029.6       0   166.7
Permanent Ineff=
       F       F
Bank Sta=4995.8,5003.2
Exp/Cntr=0.5,0.3

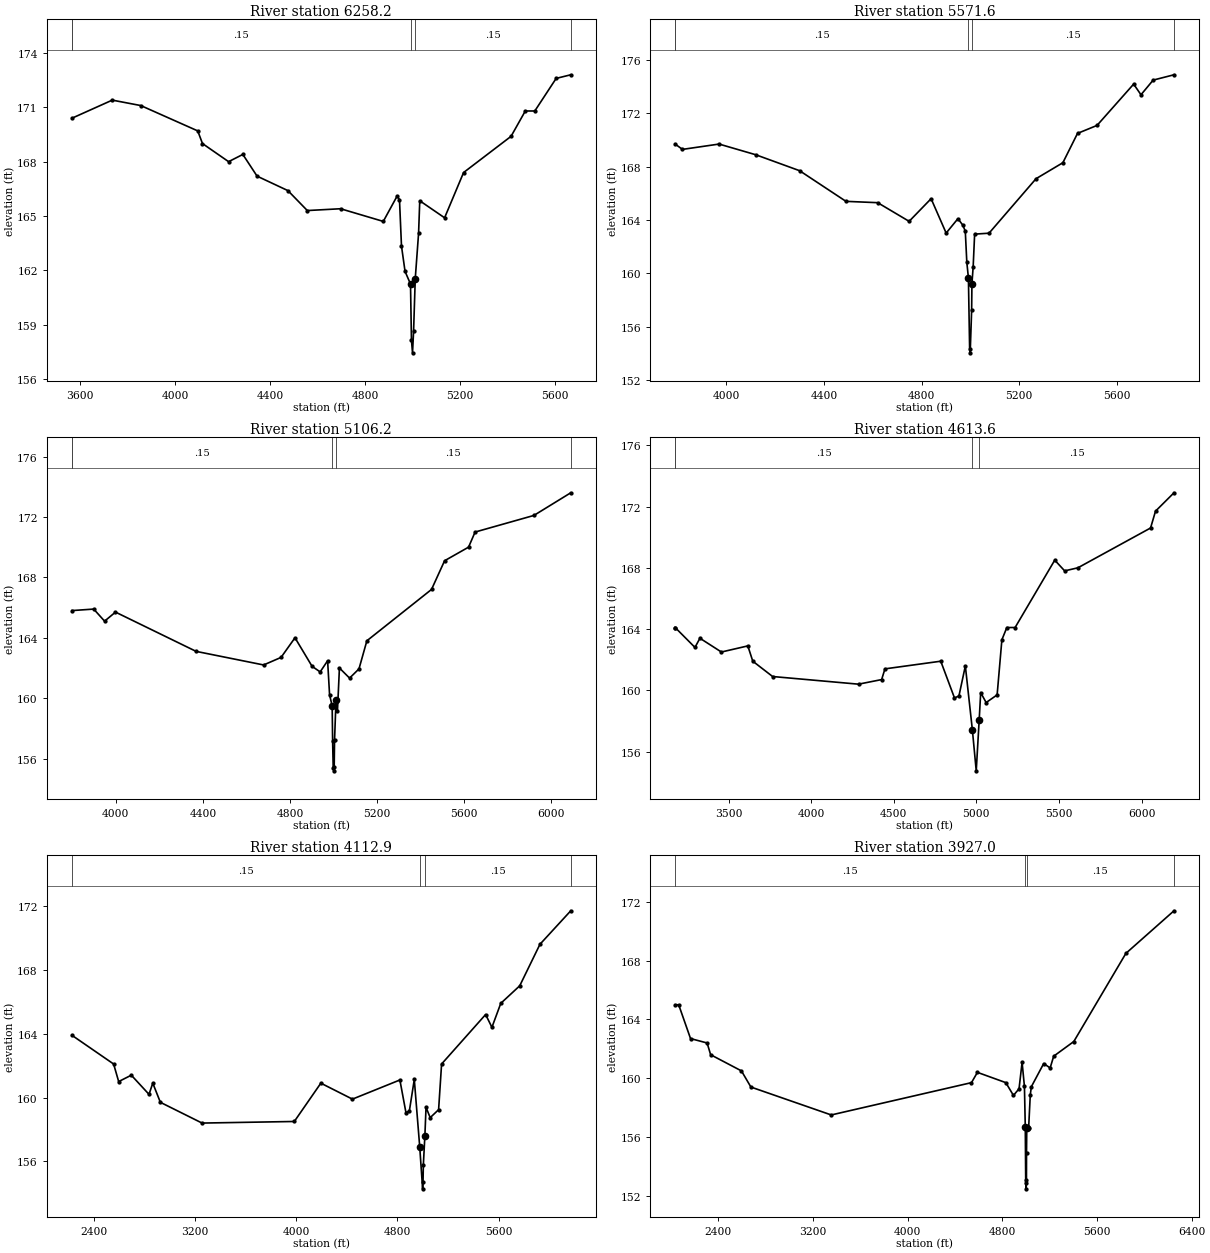
Type RM Length L Ch R = 1 ,6258.2  ,622.65,686.6,682.85
BEGIN DESCRIPTION:
Cross Section XS-02.3-Bridge1-exp
END DESCRIPTION:
XS GIS Cut Line= 4
      3031821.47      13951944.7      3030885.67      13951840.7
       3030460.8      13951786.3      3029830.52       13951415.
#Sta/Elev= 30
  3565.2   170.4  3735.2   171.4  3855.2   171.1  4095.2   169.7  4115.2     169
  4225.2     168  4285.2   168.4  4345.2   167.2  4475.2   166.4  4556.8   165.3
  4696.8   165.4  4876.8   164.7  4935.1   166.1  4945.1   165.9  4953.5  163.34
  4968.5  161.94  4991.5  161.24  4995.5  158.14    5000  157.44  5004.5  158.64
  5011.5  161.54  5025.5  164.04  5030.5  165.84  5135.1   164.9  5215.1   167.4
  5415.1   169.4  5475.1   170.8  5515.1   170.8  5605.1   172.6  5666.6   172.8
#Mann= 5 , 1 , 0
  3565.2      .2       0  3565.2     .15       0  4991.5     .07       0
  5011.5     .15       0  5666.6      .2       0
Bank Sta=4991.5,5011.5
Exp/Cntr=0.3,0.1

Type RM Length L Ch R = 1 ,5571.6  ,472.8,465.4,458.01
BEGIN DESCRIPTION:
Cross Section XS-02
END DESCRIPTION:
XS GIS Cut Line= 3
      3031890.97      13951930.3      3031072.62      13951450.2
      3030265.48      13950709.7
#Sta/Elev= 30
  3790.5   169.7  3820.5   169.3  3970.5   169.7  4120.5   168.9  4300.5   167.7
  4490.5   165.4  4620.5   165.3  4749.3   163.9  4839.3   165.6    4901  163.02
  4949.3   164.1  4968.6  163.63  4979.4  163.17  4985.7  160.82  4992.2  159.67
  4997.2  154.35  4999.5  154.03  5005.5  157.25  5006.6  159.21  5011.7  160.49
  5017.7  162.94  5076.7  163.01  5269.3   167.1  5379.3   168.3  5439.3   170.5
  5519.3   171.1  5669.3   174.2  5699.3   173.4  5749.3   174.5  5834.6   174.9
#Mann= 5 , 1 , 0
  3790.5      .2       0  3790.5     .15       0  4992.2     .07       0
  5006.6     .15       0  5834.6      .2       0
Bank Sta=4992.2,5006.6
Exp/Cntr=0.3,0.1

Type RM Length L Ch R = 1 ,5106.2  ,567.67,492.6,440.29
BEGIN DESCRIPTION:
Cross Section XS-01.5
END DESCRIPTION:
XS GIS Cut Line= 4
      3032086.25      13951757.1      3031352.48      13951071.9
      3031042.92      13950807.9      3030296.34      13950343.5
#Sta/Elev= 30
  3798.8   165.8  3898.8   165.9  3948.8   165.1  3998.8   165.7  4368.8   163.1
  4678.8   162.2  4758.8   162.7  4822.8     164  4901.3  162.11  4938.4  161.74
  4972.6  162.48  4981.6  160.22  4993.5  159.49  4995.6  157.15  4998.3  155.38
  5001.3  155.19  5002.8  155.45  5004.4   157.2  5011.2  159.91  5017.8  159.16
  5026.8     162  5073.4  161.33  5116.6  161.94  5152.8   163.8  5449.6   167.2
  5509.6   169.1  5619.6     170  5649.6     171  5919.6   172.1  6088.8   173.6
#Mann= 5 , 1 , 0
  3798.8      .2       0  3798.8     .15       0  4993.5     .07       0
  5011.2     .15       0  6088.8      .2       0
Bank Sta=4993.5,5011.2
Exp/Cntr=0.3,0.1

Type RM Length L Ch R = 1 ,4613.6  ,525.94,500.7,478.94
BEGIN DESCRIPTION:
Cross Section XS01.4
END DESCRIPTION:
XS GIS Cut Line= 3
      3032644.11      13951793.6      3031705.07      13950613.7
      3030260.38      13950168.3
#Sta/Elev= 30
  3176.6   164.1  3176.7   164.1  3296.6   162.8  3326.6   163.4  3456.6   162.5
  3616.6   162.9  3646.6   161.9  3766.6   160.9  4286.6   160.4  4426.6   160.7
  4446.6   161.4  4784.5   161.9  4867.6   159.5  4894.5  159.63  4933.3  161.59
  4976.1  157.39  4999.2  154.74  5017.2  158.08  5026.2  159.85  5059.1   159.2
  5125.7   159.7  5154.5   163.3  5184.5   164.1  5234.5   164.1  5474.5   168.5
  5534.5   167.8  5614.5     168  6054.5   170.6  6084.5   171.7  6196.3   172.9
#Mann= 4 , 1 , 0
  3176.6      .2       0  3176.7     .15       0  4976.1     .05       0
  5017.2     .15       0
Bank Sta=4976.1,5017.2
Exp/Cntr=0.3,0.1

Type RM Length L Ch R = 1 ,4112.9  ,139.61,185.9,192.04
BEGIN DESCRIPTION:
Cross Section XS-01c
END DESCRIPTION:
XS GIS Cut Line= 4
       3033279.5      13951936.8      3031846.42      13950054.8
       3031258.1       13950047.      3030264.59      13950018.7
#Sta/Elev= 30
  2223.8   163.9  2553.8   162.1  2593.8     161  2693.8   161.4  2833.8   160.2
  2863.8   160.9  2923.8   159.7  3253.8   158.4  3983.8   158.5  4193.8   160.9
  4443.8   159.9  4819.3   161.1  4867.6  159.04  4894.5  159.17  4933.3  161.13
  4976.1  156.93  4999.2  154.28  5002.4  154.73    5005  155.78  5017.2  157.62
  5026.2  159.39  5059.1  158.74  5125.7  159.24  5149.3   162.1  5497.7   165.2
  5547.7   164.4  5617.7   165.9  5767.7     167  5927.7   169.6  6171.6   171.7
#Mann= 4 ,-1 , 0
  2223.8     .15       0  4976.1     .05       0  5017.2     .15       0
  6171.6      .2       0
Bank Sta=4976.1,5017.2
Exp/Cntr=0.3,0.1

Type RM Length L Ch R = 1 ,3927.0  ,437.37,949.1,867.43
BEGIN DESCRIPTION:
Cross Section XS-01b
END DESCRIPTION:
XS GIS Cut Line= 5
      3033363.46      13951930.3      3032663.18      13950957.1
      3031942.66      13949942.1      3031265.72      13949840.9
        3030186.      13949721.6
#Sta/Elev= 30
  2035.7     165  2065.7     165  2165.7   162.7  2305.7   162.4  2335.7   161.6
  2595.7   160.5  2675.7   159.4  3354.7   157.5  4539.4   159.7  4589.4   160.4
  4829.4   159.7  4893.8  158.83  4941.1  159.28  4966.9  161.08  4986.7  159.44
  4993.9  156.66  4997.6  152.84  5001.3  152.47  5003.7  153.09  5004.3   154.9
  5006.4  156.62    5022  156.58  5036.2  158.89  5045.7  159.43  5149.4     161
  5203.9   160.7  5233.9   161.5  5403.9   162.5  5843.9   168.5  6250.2   171.4
#Mann= 4 ,-1 , 0
  2035.7     .15       0  4993.9     .05       0  5006.4     .15       0
  6250.2      .2       0
Bank Sta=4993.9,5006.4
Exp/Cntr=0.5,0.3