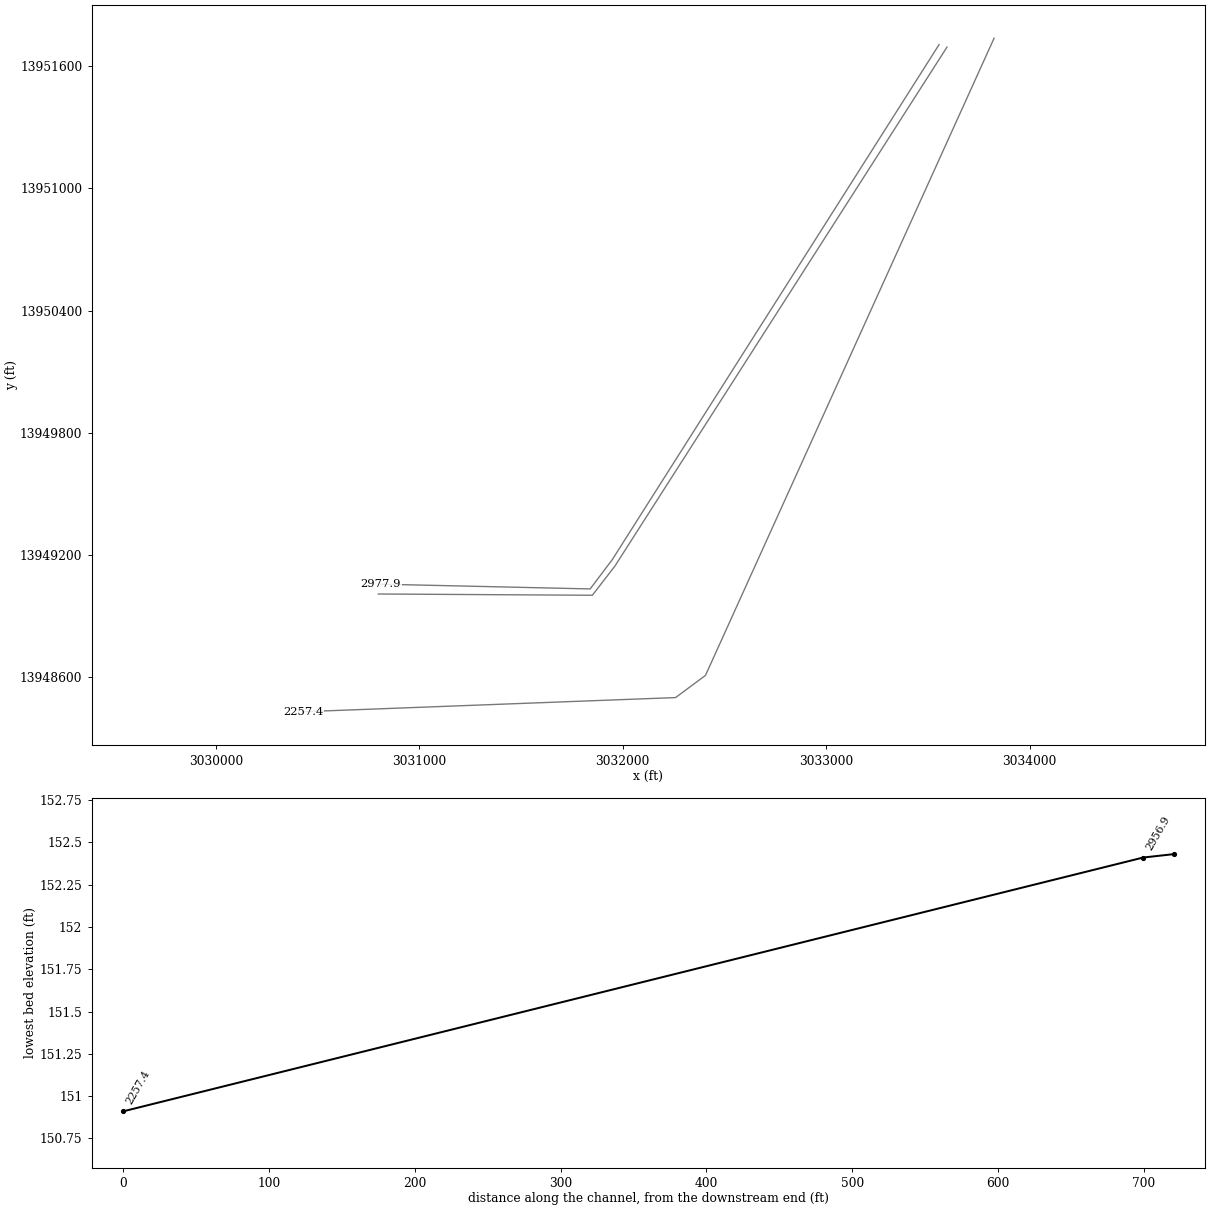
HEC-RAS study M124-00-00.PRJ: M124-00-00

--- M124-00-00.g01 (geometry) --- (continued)

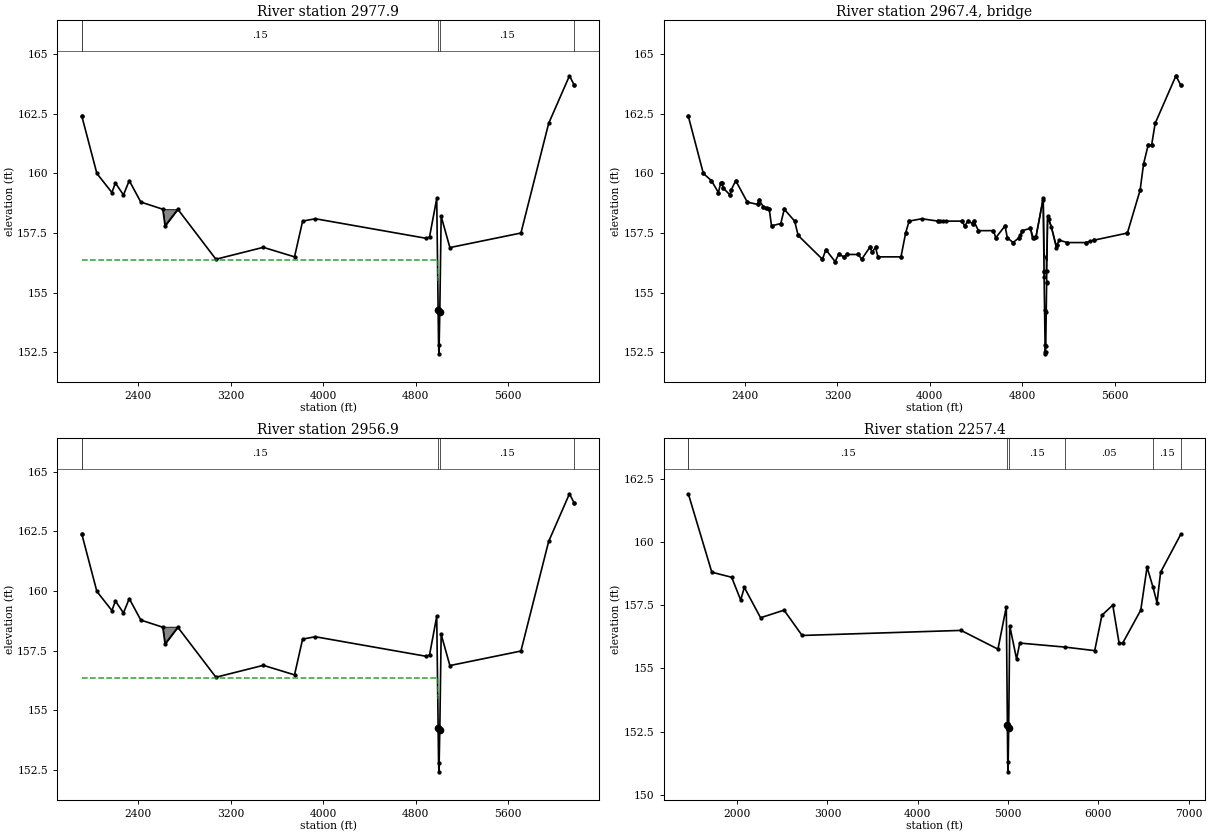
Type RM Length L Ch R = 1 ,2977.9  ,21,21,21
BEGIN DESCRIPTION:
Upstream Section of Bridge/Culvert/Weir
END DESCRIPTION:
XS GIS Cut Line= 4
      3033555.13      13951706.4      3031949.48      13949177.2
      3031840.18      13949032.2      3030810.41      13949055.6
#Sta/Elev= 30
  1910.6   162.4  1910.7   162.4  2040.6     160  2170.6   159.2  2200.7   159.6
  2270.7   159.1  2320.7   159.7  2420.6   158.8  2610.7   158.5  2630.6   157.8
  2740.7   158.5  3070.6   156.4  3480.6   156.9  3750.7   156.5  3820.6     158
  3930.7   158.1 4888.66  157.28 4918.46  157.33 4981.06  158.95 4993.16  154.29
 4996.86  152.81 5000.46  152.43 5007.46  154.17 5019.36   158.2 5094.86  156.89
  5709.5   157.5  5949.4   162.1  6129.4   164.1  6171.4   163.7  6171.5   163.7
#Mann= 5 ,-1 , 0
  1910.6      .2       0  1910.7     .15       0 4993.16     .05       0
 5007.46     .15       0  6171.4      .2       0
#XS Ineff= 2 , 0
       0    4990  156.35 5017.46       0  156.35
Permanent Ineff=
       F       F
#Block Obstruct= 2 , 0
       0    2740   158.5               0
Bank Sta=4993.16,5007.46
Exp/Cntr=0.5,0.3

Type RM Length L Ch R = 3 ,2967.4  ,,,
BEGIN DESCRIPTION:
PL1_M124-00-00-X01a
END DESCRIPTION:
Bridge Culvert--1,0,-1,-1, 0
Deck Dist Width WeirC Skew NumUp NumDn MinLoCord MaxHiCord MaxSubmerge Is_Ogee
10,1,2.6,0, 25, 25, , , 0.95, 0, 1,1,,
  4870.7 4888.66  4900.7  4910.7 4918.46 4978.66 4981.06 4988.37 4988.46 4988.96
 4993.16 4996.86 4998.16 5000.46 5001.56 5003.16 5007.46 5010.55 5010.66 5011.86
 5019.36 5028.66 5051.76 5094.86    5099
   157.7   157.4  157.31  157.33  157.34   158.9  158.96  156.62  156.62  156.61
  156.56  156.52  156.51  156.48  156.47  156.45   156.4  156.37  156.37  156.35
  158.21  158.08  157.76  156.95     157
                                          158.89  158.95  155.89  155.85  155.78
  155.73  155.69  155.68  155.65  155.64  155.62  155.57  155.54  155.44  155.92
   158.2
  4870.7 4888.66  4900.7  4910.7 4918.46 4978.66 4981.06 4988.37 4988.46 4988.96
 4993.16 4996.86 4998.16 5000.46 5001.56 5003.16 5007.46 5010.55 5010.66 5011.86
 5019.36 5028.66 5051.76 5094.86    5099
  157.68   157.4  157.31  157.33  157.34   158.9  158.96  156.62  156.62  156.61
  156.56  156.52  156.51  156.48  156.47  156.45   156.4  156.37  156.37  156.35
  158.21  158.08  157.76  156.95  156.98
                                          158.89  158.95  155.89  155.85  155.78
  155.73  155.69  155.68  155.65  155.64  155.62  155.57  155.54  155.44  155.92
   158.2
BR Coef= 1 , 1 , 0 ,1.25, 0 ,,,0.8,-1,2,1,
WSPro=,,,, 1 ,,,, 0 ,,,, 0 ,,,,-1 ,-1 ,-1 , 0 , 0 , 0 , 0 , 0
BR U #Sta/Elev= 156
  1910.6   162.4  1910.7   162.4  2040.6     160  2040.7     160  2110.6   159.7
  2110.7   159.7  2170.6   159.2  2170.7   159.2  2190.6   159.6  2190.7   159.6
  2200.6   159.6  2200.7   159.6  2210.6   159.4  2210.7   159.4  2270.6   159.1
  2270.7   159.1  2280.6   159.3  2280.7   159.3  2320.6   159.7  2320.7   159.7
  2420.6   158.8  2420.7   158.8  2510.6   158.7  2510.7   158.7  2520.6   158.9
  2520.7   158.9  2560.6   158.6  2560.7   158.6  2580.7  158.56  2590.7  158.54
  2610.6   158.5  2610.7   158.5  2630.6   157.8  2630.7   157.8  2710.6   157.9
  2710.7   157.9  2740.6   158.5  2740.7   158.5  2830.6     158  2830.7     158
  2860.6   157.4  2860.7   157.4  3070.6   156.4  3070.7   156.4  3100.6   156.8
  3100.7   156.8  3180.6   156.3  3180.7   156.3  3210.6   156.6  3210.7   156.6
  3260.6   156.5  3260.7   156.5  3280.6   156.6  3280.7   156.6  3380.6   156.6
  3380.7   156.6  3410.6   156.4  3410.7   156.4  3480.6   156.9  3480.7   156.9
  3500.6   156.7  3500.7   156.7  3530.6   156.9  3530.7   156.9  3550.6   156.5
  3550.7   156.5  3750.6   156.5  3750.7   156.5  3790.6   157.5  3790.7   157.5
  3820.6     158  3820.7     158  3930.7   158.1  4070.6     158  4070.7     158
  4090.7     158  4110.7     158  4140.7     158  4280.6     158  4280.7     158
  4300.6   157.8  4300.7   157.8  4330.6     158  4330.7     158  4370.6   157.9
  4370.7   157.9  4380.6     158  4380.7     158  4420.6   157.6  4420.7   157.6
  4550.6   157.6  4550.7   157.6  4570.6   157.3  4570.7   157.3  4650.6   157.8
  4650.7   157.8  4670.6   157.3  4670.7   157.3  4720.6   157.1  4720.7   157.1
  4770.6   157.3  4770.7   157.3  4780.7   157.4  4800.6   157.6  4800.7   157.6
  4870.6   157.7  4870.7   157.7 4888.66  157.28  4900.7   157.3  4910.7  157.32
 4918.46  157.33 4978.66  158.89 4981.06  158.95 4988.37  155.89 4988.46  155.85
 4988.96  155.64 4993.16  154.29 4996.86  152.81 4998.16  152.52 5000.46  152.43
 5001.56   152.5 5003.16  152.77 5007.46  154.17 5010.55   155.4 5010.66  155.44
 5011.86  155.92 5019.36   158.2 5028.66  158.07 5051.76  157.75 5094.86  156.89
    5099     157  5099.1     157  5119.5   157.2  5189.4   157.1  5189.5   157.1
  5349.4   157.1  5349.5   157.1  5389.5  157.16  5419.4   157.2  5419.5   157.2
  5709.4   157.5  5709.5   157.5  5819.4   159.3  5819.5   159.3  5849.4   160.4
  5849.5   160.4  5889.4   161.2  5889.5   161.2  5919.4   161.2  5919.5   161.2
  5949.4   162.1  5949.5   162.1  6129.4   164.1  6129.5   164.1  6171.4   163.7
  6171.5   163.7
BR U #Mann= 5
  1910.6      .2  1910.7     .15 4993.16    .045 5007.46     .15  6171.4      .2
BR D #Sta/Elev= 157
  1910.6  162.38  1910.7  162.38  2040.6  159.98  2040.7  159.98  2110.6  159.68
  2110.7  159.68  2170.6  159.18  2170.7  159.18  2190.6  159.58  2190.7  159.58
  2200.6  159.58  2200.7  159.58  2210.6  159.38  2210.7  159.38  2270.6  159.08
  2270.7  159.08  2280.6  159.28  2280.7  159.28  2320.6  159.68  2320.7  159.68
  2420.6  158.78  2420.7  158.78  2510.6  158.68  2510.7  158.68  2520.6  158.88
  2520.7  158.88  2560.6  158.58  2560.7  158.58  2580.7  158.54  2590.7  158.52
  2610.6  158.48  2610.7  158.48  2630.6  157.78  2630.7  157.78  2710.6  157.88
  2710.7  157.88  2740.6  158.48  2740.7  158.48  2830.6  157.98  2830.7  157.98
  2860.6  157.38  2860.7  157.38  3070.6  156.38  3070.7  156.38  3100.6  156.78
  3100.7  156.78  3180.6  156.28  3180.7  156.28  3210.6  156.58  3210.7  156.58
  3260.6  156.48  3260.7  156.48  3280.6  156.58  3280.7  156.58  3380.6  156.58
  3380.7  156.58  3410.6  156.38  3410.7  156.38  3480.6  156.88  3480.7  156.88
  3500.6  156.68  3500.7  156.68  3530.6  156.88  3530.7  156.88  3550.6  156.48
  3550.7  156.48  3750.6  156.48  3750.7  156.48  3790.6  157.48  3790.7  157.48
  3820.6  157.98  3820.7  157.98  3930.6  158.08  3930.7  158.08  4070.6  157.98
  4070.7  157.98  4090.7  157.98  4110.7  157.98  4140.7  157.98  4280.6  157.98
  4280.7  157.98  4300.6  157.78  4300.7  157.78  4330.6  157.98  4330.7  157.98
  4370.6  157.88  4370.7  157.88  4380.6  157.98  4380.7  157.98  4420.6  157.58
  4420.7  157.58  4550.6  157.58  4550.7  157.58  4570.6  157.28  4570.7  157.28
  4650.6  157.78  4650.7  157.78  4670.6  157.28  4670.7  157.28  4720.6  157.08
  4720.7  157.08  4770.6  157.28  4770.7  157.28  4780.7  157.38  4800.6  157.58
  4800.7  157.58  4870.6  157.68  4870.7  157.68 4888.66  157.26  4900.7  157.28
  4910.7   157.3 4918.46  157.31 4978.66  158.87 4981.06  158.93 4988.37  155.87
 4988.46  155.83 4988.96  155.62 4993.16  154.27 4996.86  152.79 4998.16   152.5
 5000.46  152.41 5001.56  152.48 5003.16  152.75 5007.46  154.15 5010.55  155.38
 5010.66  155.42 5011.86   155.9 5019.36  158.18 5028.66  158.05 5051.76  157.73
 5094.86  156.87    5099  156.98  5099.1  156.98  5119.5  157.18  5189.4  157.08
  5189.5  157.08  5349.4  157.08  5349.5  157.08  5389.5  157.14  5419.4  157.18
  5419.5  157.18  5709.4  157.48  5709.5  157.48  5819.4  159.28  5819.5  159.28
  5849.4  160.38  5849.5  160.38  5889.4  161.18  5889.5  161.18  5919.4  161.18
  5919.5  161.18  5949.4  162.08  5949.5  162.08  6129.4  164.08  6129.5  164.08
  6171.4  163.68  6171.5  163.68
BR D #Mann= 5
  1910.6      .2  1910.7     .15 4993.16    .045 5007.46     .15  6171.4      .2
BC Design=,, 0 ,, 0 ,,,,,,
BC HTab HWMax=164.1

Type RM Length L Ch R = 1 ,2956.9  ,699.5,699.5,699.5
BEGIN DESCRIPTION:
Downstream Section of Bridge/Culvert/Weir
END DESCRIPTION:
XS GIS Cut Line= 4
      3033594.11      13951694.2      3031961.24      13949143.7
      3031850.79      13949001.1      3030798.83      13949007.3
#Sta/Elev= 30
  1910.6  162.38  1910.7  162.38  2040.6  159.98  2170.6  159.18  2200.7  159.58
  2270.7  159.08  2320.7  159.68  2420.6  158.78  2610.7  158.48  2630.6  157.78
  2740.7  158.48  3070.6  156.38  3480.6  156.88  3750.7  156.48  3820.6  157.98
  3930.6  158.08 4888.66  157.26 4918.46  157.31 4981.06  158.93 4993.16  154.27
 4996.86  152.79 5000.46  152.41 5007.46  154.15 5019.36  158.18 5094.86  156.87
  5709.5  157.48  5949.4  162.08  6129.4  164.08  6171.4  163.68  6171.5  163.68
#Mann= 5 ,-1 , 0
  1910.6      .2       0  1910.7     .15       0 4993.16     .05       0
 5007.46     .15       0  6171.4      .2       0
#XS Ineff= 2 , 0
       0    4990  156.35 5014.13       0  156.35
Permanent Ineff=
       F       F
#Block Obstruct= 2 , 0
       0  2740.8   158.5               0
Bank Sta=4993.16,5007.46
Exp/Cntr=0.5,0.3

Type RM Length L Ch R = 1 ,2257.4  ,0,0,0
BEGIN DESCRIPTION:
Cross Section XS-01
END DESCRIPTION:
XS GIS Cut Line= 4
       3033825.5      13951737.7       3032407.1      13948607.5
      3032260.01      13948498.4      3030428.08      13948428.8
#Sta/Elev= 30
  1460.2   161.9  1720.2   158.8  1940.2   158.6  2040.2   157.7  2080.2   158.2
  2260.2     157  2520.2   157.3  2720.2   156.3  4480.2   156.5 4888.66  155.76
 4981.06  157.43 4993.16  152.77 4996.86  151.29 5000.46  150.91 5007.46  152.65
 5019.36  156.68 5094.86  155.37  5129.9     156  5632.3  155.84  5959.9   155.7
  6039.9   157.1  6159.9   157.5  6229.9     156  6269.9     156  6469.9   157.3
  6539.9     159  6603.6  158.23  6649.9   157.6  6689.9   158.8  6913.2   160.3
#Mann= 7 , 1 , 0
  1460.2      .2       0  1460.2     .15       0 4993.16     .05       0
 5007.46     .15       0  5632.3     .05       0  6603.6     .15       0
  6913.2      .2       0
Bank Sta=4993.16,5007.46
Exp/Cntr=0.3,0.1

Chan Stop Cuts=-1
Use User Specified Reach Order=0
User Specified Reach Order=M124-00-00      ,Reach - 1